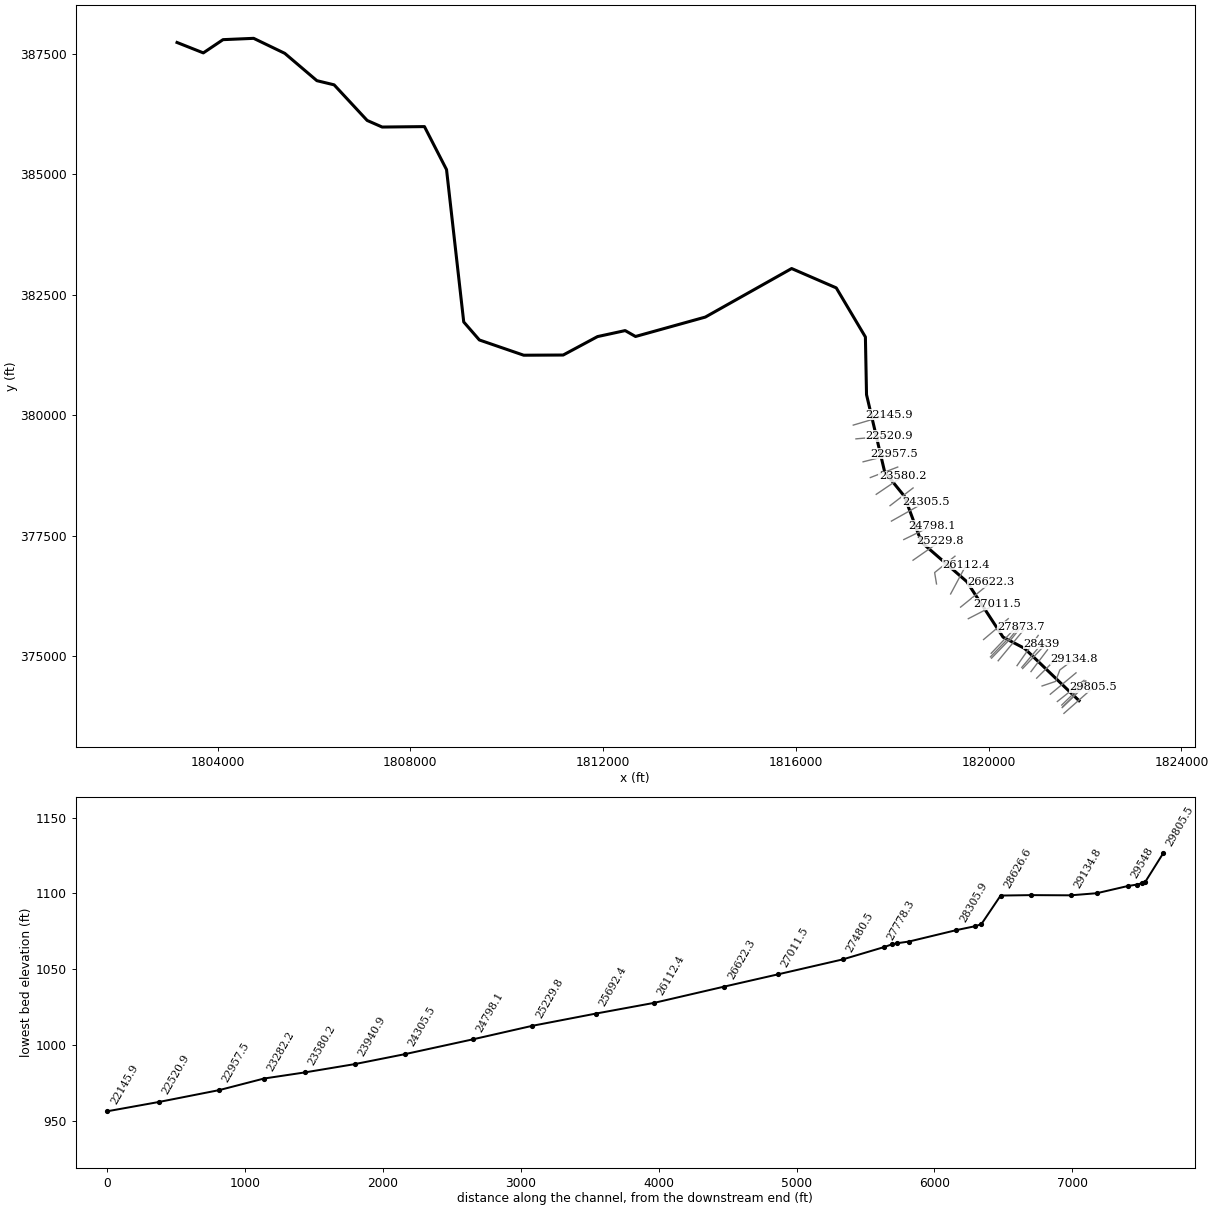
--- WHITEOAKCK.prj (project) ---

Proj Title=WHITEOAKCK
Current Plan=p01
Default Exp/Contr=0,0
English Units
Geom File=g01
Flow File=f01
Plan File=p01
BEGIN DESCRIPTION:
END DESCRIPTION:
DSS Export Rating Curves= 0
DSS Export Rating Curve Sorted= 0
DSS Export Volume Flow Curves= 0
DXF OffsetX= 0
DXF OffsetY= 0
DXF ScaleX= 0
DXF ScaleY= 0

--- WHITEOAKCK.p01 (plan) ---

Plan Title=Floodplain
Program Version=4.00
Geom File=g01
Flow File=f01
K Sum by GR=0
Std Step Tol=0.01
Critical Tol=0.01
Num of Std Step Trials=20
Max Error Tol=0.3
Flow Tol Ratio=0.001
Split Flow NTrial=30
Split Flow Tol=0.02
Split Flow Ratio=0.02
Log Output Level=0
Friction Slope Method=1
Unsteady Friction Slope Method=2
Unsteady Bridges Friction Slope Method=1
Global Log Level=0
CheckData=False
Run HTab=0
Run UNet=0
Run PostProcess=0
UNET Theta=0
UNET Theta Warmup=0
UNET ZTol=0
UNET ZSATol=0
UNET MxIter=0
UNET MaxInSteps=0
UNET DtIC=0
UNET DtMin=0
UNET MaxCRTS=0
UNET WFStab=0
UNET SFStab=0
UNET WFX=0
UNET SFX=0
UNET DSS MLevel=0
UNET DZMax Abort=0
UNET Convert EG Bridges=0
UNET Use Existing IB Tables=0
UNET Froude Limit=0
UNET Froude Power=0
Write IC File=0
Echo Input=False
Echo Output=False
Write Detailed=0

--- WHITEOAKCK.f01 (steady flow) ---

Flow Title=NFF Regression Equation
Program Version=4.10
Number of Profiles= 1
Profile Names=P100yr
River Rch & RM=WHITEOAKCK,Main            ,29805.5
 1203.16
River Rch & RM=WHITEOAKCK,Main            ,25692.4
1338.975
River Rch & RM=WHITEOAKCK,Main            ,24798.1
 1766.99
River Rch & RM=WHITEOAKCK,Main            ,18991.4
1887.897
River Rch & RM=WHITEOAKCK,Main            ,18072
3063.933
River Rch & RM=WHITEOAKCK,Main            ,14523.1
3274.366
River Rch & RM=WHITEOAKCK,Main            ,7266.9
3668.294
Boundary for River Rch & Prof#=WHITEOAKCK,Main            , 1
Up Type= 0
Dn Type= 3
Dn Slope=0.004
DSS Import GetInterval= 0
DSS Import GetPeak= 0
DSS Import FillOption= 0

--- WHITEOAKCK.g01 (geometry) ---

Geom Title=USGS 10m DEM
Program Version=4.10

River Reach=WHITEOAKCK      ,Main
Reach XY= 30
     1821876.555      374072.443     1820745.881      375157.641
       1820299.7      375391.039     1819546.228      376543.817
     1818606.124      377360.657     1818252.825      378313.782
     1817842.235      378822.029     1817466.367      380423.331
     1817442.929      381620.119     1816837.894      382639.216
     1815912.113      383040.475     1814121.749      382033.313
      1812672.53      381630.319     1812457.686      381752.715
     1811883.731      381628.102     1811171.228      381245.553
     1810352.217      381241.647     1809431.645      381558.053
     1809107.426      381931.751     1808750.655       385093.21
     1808292.564      385985.775     1807414.961      385976.661
     1807103.762       386113.38     1806417.804      386852.531
     1806060.143        386938.9     1805393.476      387506.348
     1804747.643      387817.546     1804112.226      387790.203
     1803703.372      387515.463     1803157.799      387731.608

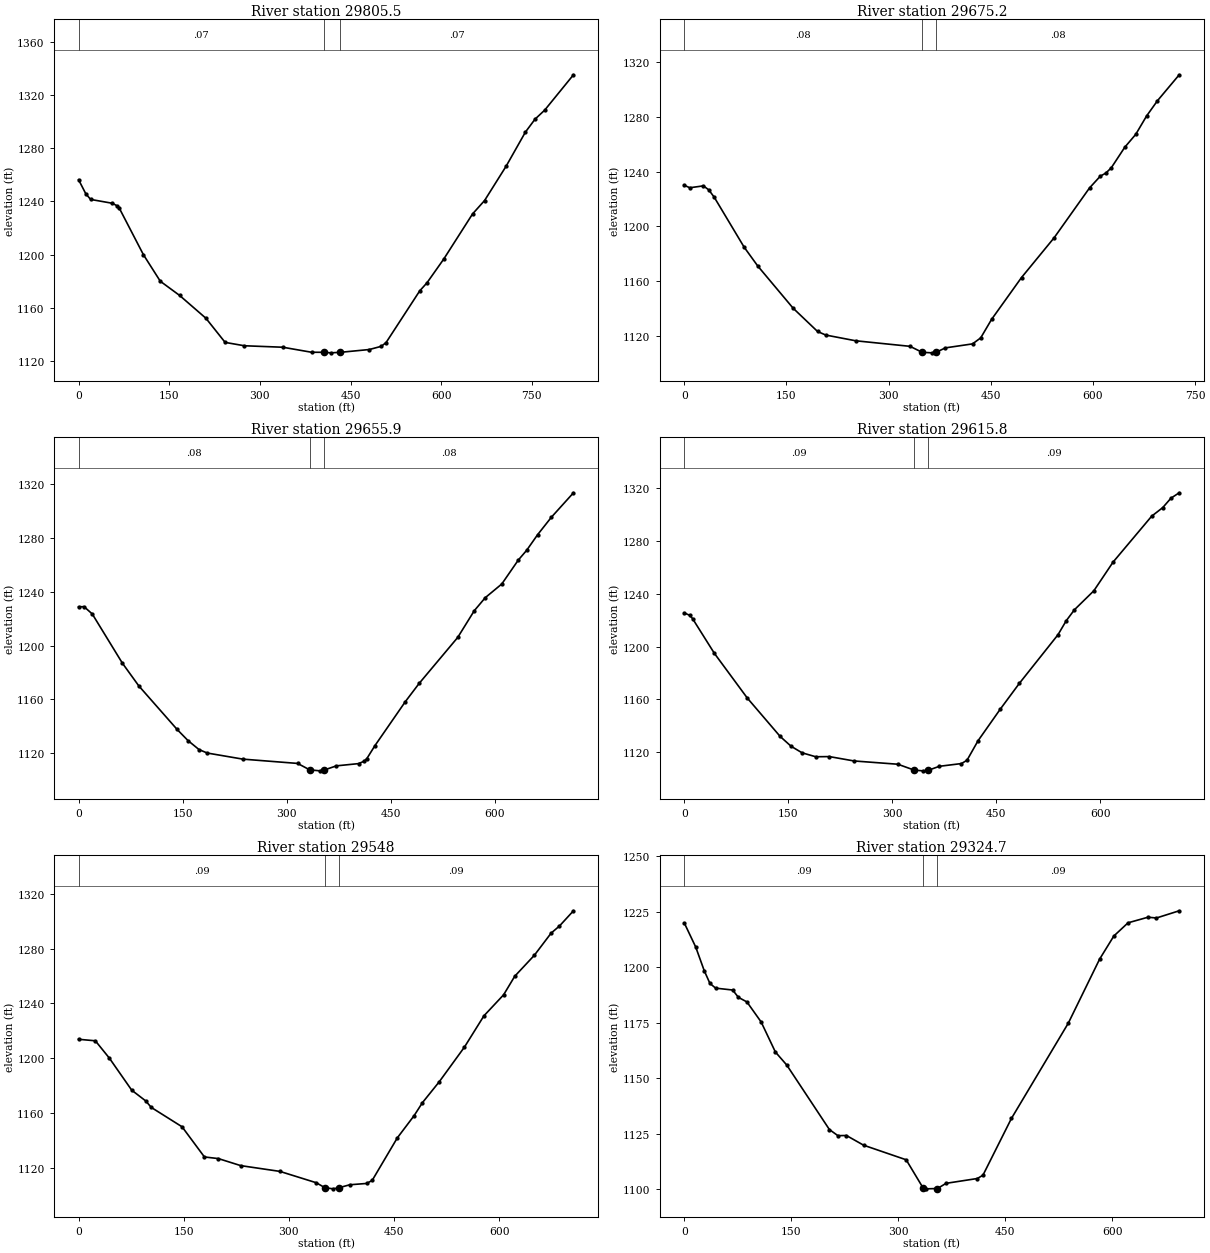
Type RM Length L Ch R = 1 ,29805.5 ,129.1,130.2,131.4
XS GIS Cut Line= 3
     1821562.822      373809.076      1821869.94      374079.943
     1822177.059      374350.809
#Sta/Elev= 30
       0 1256.31    11.9 1245.81    19.9 1241.55    55.7 1238.67    63.6  1236.8
    67.6 1234.77   107.3 1200.03   135.2 1180.12     167 1169.52   210.7 1152.33
   242.5  1134.2   274.3 1131.68   337.9 1130.57   385.6 1126.79   405.5 1126.77
   417.4 1126.36   433.4 1126.76   481.1 1128.85   500.9 1131.25   508.9  1134.1
   564.6 1172.93   576.5 1178.91   604.3 1196.77     652 1230.67   671.9 1240.74
   707.7 1266.62   739.5 1292.14   755.4 1301.83   771.3 1308.56     819 1335.14
#Mann= 3 , 0 , 0
       0     .07       0   405.5    .045       0   433.4     .07       0
Bank Sta=405.5,433.4
XS Rating Curve= 0 ,0
Exp/Cntr=0.3,0.1

Type RM Length L Ch R = 1 ,29675.2 ,9.1,19.3,29.7
XS GIS Cut Line= 2
     1821526.256      373928.982      1822049.26      374433.539
#Sta/Elev= 30
       0 1229.98       8 1228.21      28 1229.58    35.9 1226.64    43.9 1221.28
    87.8 1184.76   107.8 1170.97   159.7 1140.12   195.6 1123.09   207.6 1120.47
   251.6 1116.27   331.4 1112.21   349.2 1107.85   363.4 1107.45   369.2 1107.72
   383.3 1111.08   423.2    1114   435.2  1118.4   451.2 1131.95   495.1 1162.53
     543 1191.62     595 1228.08   610.9 1236.72   618.9 1238.92   626.9 1242.78
   646.8 1257.87   662.8 1267.22   678.8 1280.71   694.8  1291.9   726.7 1310.84
#Mann= 3 , 0 , 0
       0     .08       0   349.2    .045       0   369.2     .08       0
Bank Sta=349.2,369.2
XS Rating Curve= 0 ,0
Exp/Cntr=0.3,0.1

Type RM Length L Ch R = 1 ,29655.9 ,40.2,40.1,40.2
XS GIS Cut Line= 4
     1821539.277      373946.994     1821755.206      374155.327
     1821793.183      374234.537     1822038.409      374449.381
#Sta/Elev= 30
       0 1228.81     7.9 1228.89    19.7 1223.48    63.2 1186.85    86.9 1169.94
   142.1 1137.59   157.9 1129.26   173.7 1122.62   185.6 1120.03   236.9  1115.5
     316  1112.3   333.3 1107.54     348 1106.79   353.3 1107.23   371.9  1110.5
   403.8 1112.16   411.8 1113.92   415.7  1115.8   427.6 1125.63   471.4  1158.3
   491.3 1171.84   546.9 1206.01   570.8  1225.9   586.7 1235.61   610.5 1245.78
   634.4 1263.64   646.3 1270.78   662.2 1282.47   682.1 1295.47   713.9 1313.61
#Mann= 3 , 0 , 0
       0     .08       0   333.3    .045       0   353.3     .08       0
Bank Sta=333.3,353.3
XS Rating Curve= 0 ,0
Exp/Cntr=0.3,0.1

Type RM Length L Ch R = 1 ,29615.8 ,80.3,67.9,54.7
XS GIS Cut Line= 4
     1821517.576      373981.716     1821733.504       374190.05
     1821771.482       374269.26     1822016.707      374484.103
#Sta/Elev= 30
       0 1225.53     7.9 1223.68    11.8 1221.26    43.4 1194.83    90.8 1161.01
   138.2  1131.9     154 1124.44   169.8 1119.49   189.5 1116.49   209.2 1116.61
   244.8  1113.3     308 1110.82   331.7 1106.35     344 1105.81   351.7 1106.21
   367.9 1109.25   399.8 1111.33   407.8 1113.86   423.7 1128.63   455.5 1152.39
   483.3 1172.15     539 1208.98   550.9 1219.61   562.8 1227.97   590.7  1242.3
   618.5 1264.08   674.2  1298.9   690.1 1305.37     702 1312.54   713.9 1316.62
#Mann= 3 , 0 , 0
       0     .09       0   331.7    .045       0   351.7     .09       0
Bank Sta=331.7,351.7
XS Rating Curve= 0 ,0
Exp/Cntr=0.3,0.1

Type RM Length L Ch R = 1 ,29548   ,222.7,223.3,224
XS GIS Cut Line= 2
      1821426.43      374055.501     1821979.815      374493.869
#Sta/Elev= 30
       0 1213.89    23.9 1212.78    43.9 1200.13    75.8 1176.76    95.7 1168.96
   103.7 1164.19   147.6 1150.07   179.5 1128.07   199.4 1126.88   231.3 1121.75
   287.2 1117.54     339 1109.28   351.2  1105.7     363 1104.82   371.2 1105.59
   386.9 1107.79   410.8 1108.74   418.8 1110.94   454.7    1142   478.6 1158.16
   490.6 1167.72   514.5  1182.9   550.4 1208.15   578.3 1231.03   606.3  1246.3
   622.2 1259.85   650.1  1275.1   674.1 1291.29     686 1296.49     706  1307.6
#Mann= 3 , 0 , 0
       0     .09       0   351.2    .045       0   371.2     .09       0
Bank Sta=351.2,371.2
XS Rating Curve= 0 ,0
Exp/Cntr=0.3,0.1

Type RM Length L Ch R = 1 ,29324.7 ,176.2,189.8,203.4
XS GIS Cut Line= 2
     1821279.945      374206.326     1821813.799      374650.119
#Sta/Elev= 30
       0  1219.8      16 1208.99    27.9 1198.36    35.9 1192.62    43.9  1190.5
    67.8 1189.65    75.8 1186.36    87.8 1184.28   107.7 1175.28   127.7 1161.75
   143.6 1155.89   203.5 1126.81   215.4 1124.06   227.4 1124.13   251.4 1119.77
   311.2 1113.19   335.1 1100.41   339.1 1100.11   355.1 1100.25   367.1 1102.59
     411 1104.76   418.9 1106.26   458.8  1131.8   538.6 1174.72   582.5 1203.54
   602.5 1213.98   622.4 1219.92   650.3 1222.43   662.3  1222.1   694.2 1225.34
#Mann= 3 , 0 , 0
       0     .09       0   335.1    .045       0   355.1     .09       0
Bank Sta=335.1,355.1
XS Rating Curve= 0 ,0
Exp/Cntr=0.3,0.1

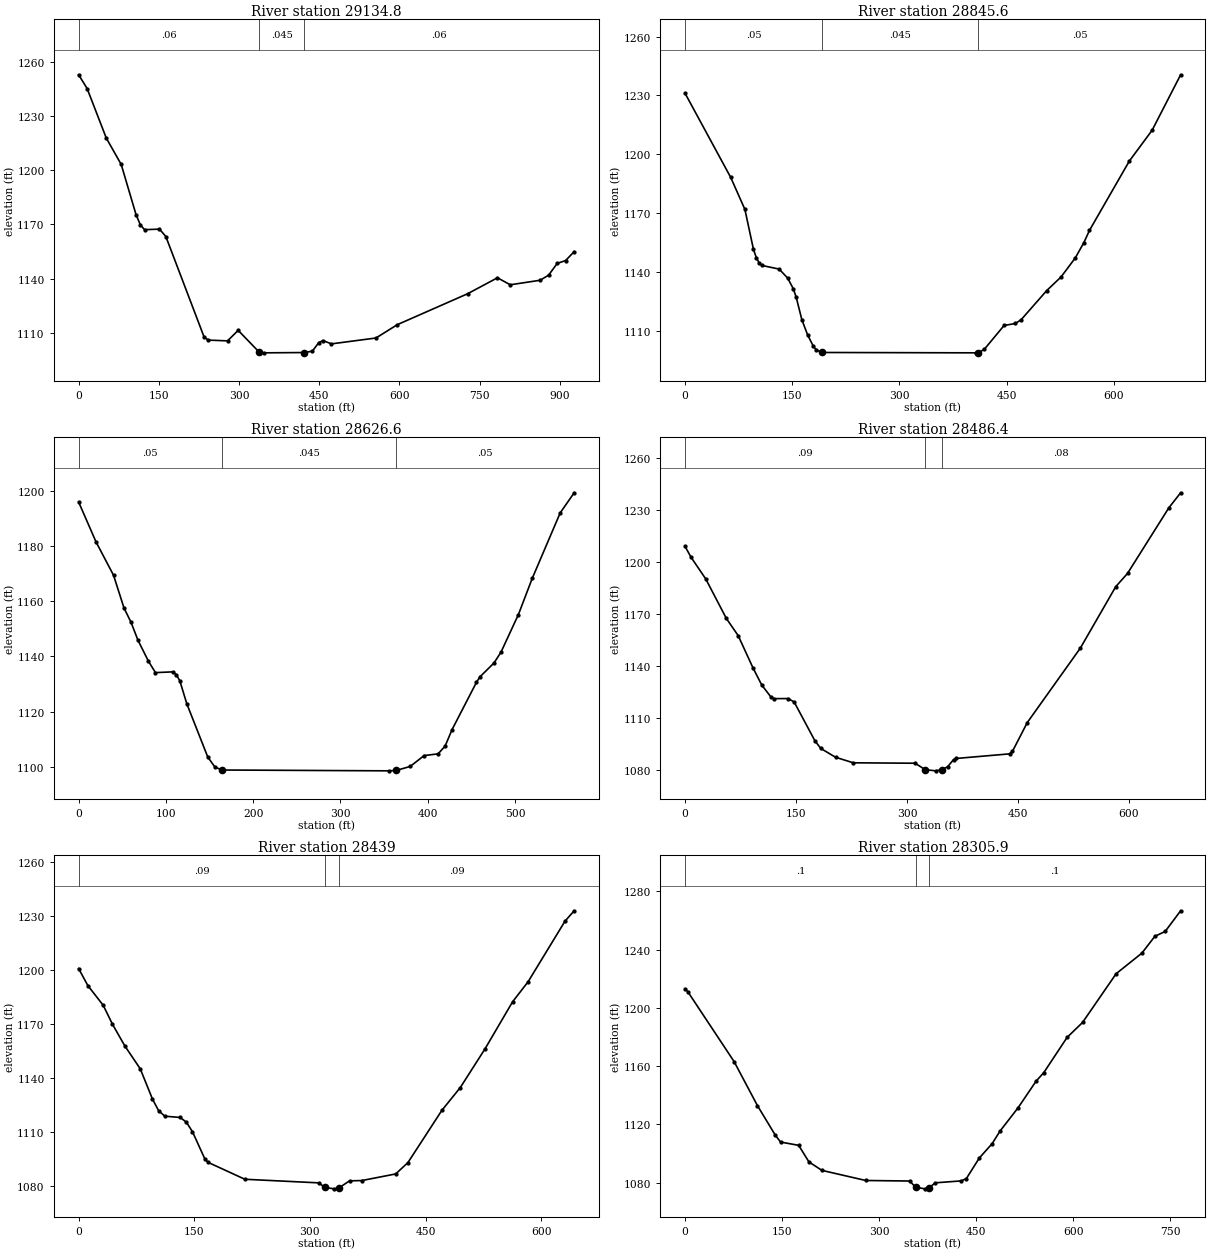
Type RM Length L Ch R = 1 ,29134.8 ,300.6,289.2,277.9
XS GIS Cut Line= 4
     1821109.589      374377.767     1821388.452      374472.168
     1821477.428      374709.798     1821779.077      374938.747
#Sta/Elev= 30
       0 1253.15    15.9 1245.51    51.7 1218.01    79.6 1203.37   107.4 1175.46
   115.4 1169.81   123.3 1167.12   151.2 1167.43   163.1 1163.33   234.7 1107.46
   242.7 1105.79   278.5 1105.37   298.4 1111.21     338 1099.01     346 1098.72
   421.3 1098.88   437.1 1099.62     449 1104.37     457 1105.55   472.8  1103.7
   556.1 1106.96     596 1114.36   727.5 1131.54   783.3  1140.4   807.3 1136.52
   863.1 1139.03     879 1141.86     895 1148.37   910.9 1149.99   926.8 1154.96
#Mann= 3 , 0 , 0
       0     .06       0     338    .045       0   421.3     .06       0
Bank Sta=338,421.3
XS Rating Curve= 0 ,0
Exp/Cntr=0.3,0.1

Type RM Length L Ch R = 1 ,28845.6 ,215.5,219,222.5
XS GIS Cut Line= 2
     1820996.742      374539.442     1821488.279      375028.808
#Sta/Elev= 30
       0 1231.03    63.8 1188.25    83.7 1171.92    95.7 1151.55    99.7 1147.32
   103.6 1144.67   107.6 1143.36   131.6 1141.52   143.5 1136.96   151.5 1131.47
   155.5 1127.18   163.4 1115.76   171.4 1108.06   179.4 1102.26   183.4 1100.44
   191.3 1099.03   406.6 1098.85   410.6 1098.97   418.6 1100.56   446.5 1112.79
   462.4  1113.8   470.4 1115.75   506.2 1130.58   526.2  1137.5   546.1 1147.18
   558.1 1154.96     566 1161.23   621.8 1196.56   653.7 1212.25   693.6  1240.5
#Mann= 3 , 0 , 0
       0     .05       0   191.3    .045       0   410.6     .05       0
Bank Sta=191.3,410.6
XS Rating Curve= 0 ,0
Exp/Cntr=0.3,0.1

Type RM Length L Ch R = 1 ,28626.6 ,143,140.2,137.5
XS GIS Cut Line= 2
     1820879.077       374675.64     1821221.959      375128.114
#Sta/Elev= 30
       0 1195.84      20 1181.36      40 1169.34      52 1157.47      60 1152.34
      68 1145.81      80 1138.22      88 1134.11     108 1134.38   111.9 1133.36
   115.9 1131.16   123.9 1122.86   147.9 1103.59   155.9 1100.02   163.9 1098.86
   355.8 1098.56   363.8  1098.7   379.8 1100.14   395.8 1104.08   411.8 1104.71
   419.8 1107.49   427.8 1113.48   455.8 1130.62   459.8 1132.59   475.8 1137.58
   483.8 1141.47   503.8 1155.11   519.7 1168.25   551.7 1191.92   567.7 1199.19
#Mann= 3 , 0 , 0
       0     .05       0   163.9    .045       0   363.8     .05       0
Bank Sta=163.9,363.8
XS Rating Curve= 0 ,0
Exp/Cntr=0.3,0.1

Type RM Length L Ch R = 1 ,28486.4 ,46.1,47.4,48.8
XS GIS Cut Line= 2
     1820706.378      374739.616     1821166.447      375226.812
#Sta/Elev= 30
       0 1209.16       8 1202.97    27.9 1190.44    55.8  1167.6    71.8 1157.68
    91.7 1139.16   103.7 1129.15   115.7 1122.48   119.7 1121.32   139.6 1121.37
   147.6 1119.31   175.5 1097.01   183.5 1092.57   203.4 1087.49   227.4 1084.28
   311.1 1084.03   324.7  1080.3     339 1079.64     347  1080.3     355 1082.01
     363  1086.1     367  1086.8   438.8 1089.44   442.7 1090.92   462.7  1107.5
   534.5 1150.51   582.3 1185.93   598.3 1193.62   654.1 1231.46   670.1 1240.16
#Mann= 3 , 0 , 0
       0     .09       0   324.7    .045       0     347     .08       0
Bank Sta=324.7,347
XS Rating Curve= 0 ,0
Exp/Cntr=0.3,0.1

Type RM Length L Ch R = 1 ,28439   ,130.6,133.1,135.3
XS GIS Cut Line= 2
     1820688.582      374764.051     1821104.164      375254.503
#Sta/Elev= 30
       0  1200.6      12 1191.12    31.9 1180.21    43.9 1169.69    59.9 1157.67
    79.9 1144.96    95.8 1128.12   103.8 1121.66   111.8 1118.64   131.8 1117.93
   139.8  1115.3   147.7 1109.99   163.7 1094.94   167.7 1093.05   215.6 1083.62
   311.4 1081.62   319.4 1079.09   331.4  1078.3   337.3 1078.72   351.4 1082.73
   367.3  1082.9   411.3 1086.57   427.2  1092.9   471.2 1121.89   495.1 1134.55
     527 1155.92     563 1182.21     583 1193.26   630.9 1226.92   642.8 1232.69
#Mann= 3 , 0 , 0
       0     .09       0   319.4    .045       0   337.3     .09       0
Bank Sta=319.4,337.3
XS Rating Curve= 0 ,0
Exp/Cntr=0.3,0.1

Type RM Length L Ch R = 1 ,28305.9 ,346.2,344.4,342.5
XS GIS Cut Line= 2
     1820589.841      374799.859     1821029.041      375427.181
#Sta/Elev= 30
       0 1212.97       4  1211.2    75.8 1163.06   111.7 1132.97   139.6 1112.47
   147.6 1107.89   175.5 1105.64   191.4 1094.25   211.4 1088.45   279.2 1081.51
     347 1081.14   356.4 1076.83   370.9 1075.78   376.4 1076.36   386.9 1079.92
   426.8 1081.24   434.7 1082.85   454.7 1096.96   474.6 1106.84   486.6 1115.37
   514.5 1131.36   542.4 1149.67   554.4 1155.58   590.3 1179.69   614.2 1189.95
   666.1 1223.41     706 1237.58   725.9 1249.06   741.9 1252.42   765.8 1266.61
#Mann= 3 , 0 , 0
       0      .1       0   356.4    .045       0   376.4      .1       0
Bank Sta=356.4,376.4
XS Rating Curve= 0 ,0
Exp/Cntr=0.3,0.1

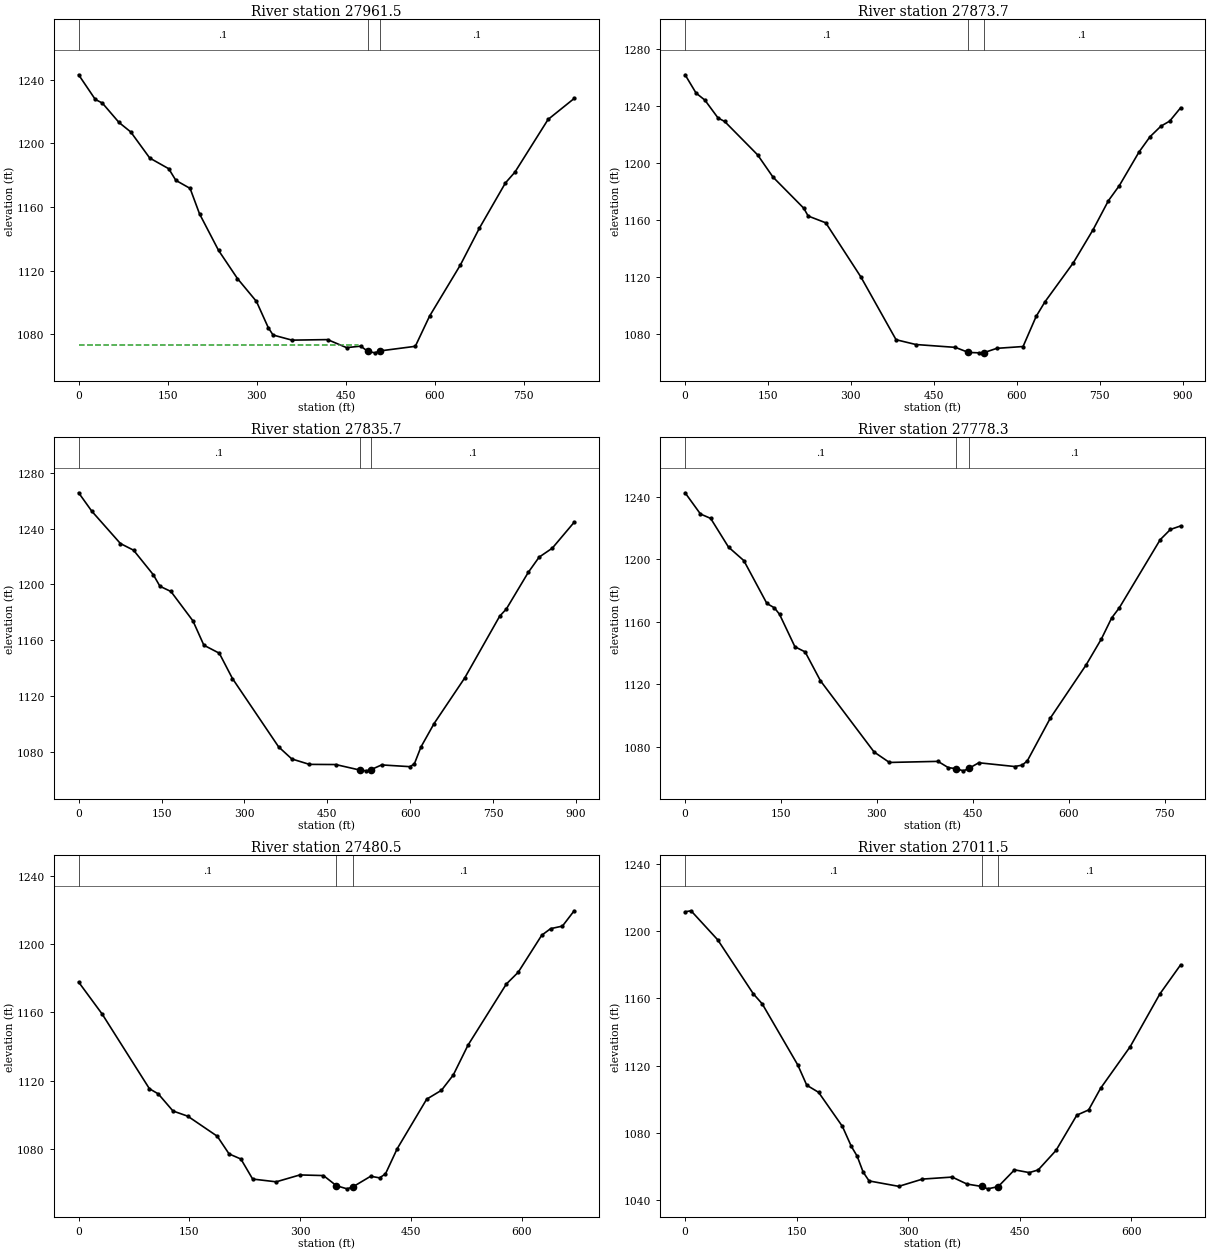
Type RM Length L Ch R = 1 ,27961.5 ,96.8,87.8,78.9
XS GIS Cut Line= 2
     1820198.131       374900.77       1820730.9      375544.216
#Sta/Elev= 30
       0 1243.23      28 1227.75      40 1225.42      68 1213.24    87.9 1207.23
   119.9 1190.82   151.9  1184.1   163.9 1176.78   187.9 1171.72   203.8 1155.71
   235.8 1132.76   267.8 1114.95   299.8 1100.56   319.8    1084   327.8 1079.44
   359.7 1076.22   419.7 1076.56   451.7 1071.51   475.6 1072.44   487.6 1069.13
   499.6 1068.23   507.6 1069.42   567.6 1072.34   591.6 1091.32   643.5 1123.48
   675.5 1146.62   719.5 1175.16   735.5 1181.94   791.4 1215.12   835.4 1228.32
#Mann= 3 , 0 , 0
       0      .1       0   487.6    .045       0   507.6      .1       0
#XS Ineff= 2 , 0
       0   471.6 1072.86               0
Permanent Ineff=
       F       F
Bank Sta=487.6,507.6
XS Rating Curve= 0 ,0
Exp/Cntr=0.3,0.1

Type RM Length L Ch R = 1 ,27873.7 ,38.7,38,38
XS GIS Cut Line= 4
     1820060.327      374955.023     1820395.614      375300.076
     1820466.143      375343.478     1820674.477       375602.81
#Sta/Elev= 30
       0  1262.1    19.9 1249.24    35.8 1244.34    59.6 1231.81    71.6 1229.35
   131.2 1205.94     159 1190.36   214.7 1168.52   222.7 1163.04   254.5 1158.29
   318.1 1120.28   381.7  1076.3   417.5 1072.94     489 1070.93   512.7 1067.37
   532.4  1067.1   540.3 1067.18   563.9 1070.25   611.5 1071.53   635.2 1092.67
   651.1 1102.87   702.5 1130.29   738.2 1153.47   765.9 1173.79   785.7 1184.39
   821.3 1207.94   841.1 1218.61   860.9 1226.05   876.8 1229.62   896.6 1238.97
#Mann= 3 , 0 , 0
       0      .1       0   512.7    .045       0   540.3      .1       0
Bank Sta=512.7,540.3
XS Rating Curve= 0 ,0
Exp/Cntr=0.3,0.1

Type RM Length L Ch R = 1 ,27835.7 ,50.5,57.4,64.2
XS GIS Cut Line= 4
     1820037.541      374981.065     1820372.827      375326.117
     1820443.357       375369.52      1820651.69      375628.852
#Sta/Elev= 30
       0 1265.78    23.9 1252.53    75.6 1229.37    99.4 1224.58   135.2 1206.95
   147.1 1198.71     167 1194.97   206.8  1173.9   226.6 1156.42   254.5 1150.69
   278.3 1132.53   361.8 1083.52   385.7 1074.83   417.5 1070.94   465.2 1070.81
   508.7 1066.87   520.6  1066.3   528.4 1067.05   548.2 1070.55   599.6 1069.29
   607.5 1071.35   619.4 1083.43   643.1  1100.2   698.6 1132.96   761.9  1177.3
   773.8 1182.35   813.4 1208.59   833.2 1219.61     857 1226.04   896.6 1244.64
#Mann= 3 , 0 , 0
       0      .1       0   508.7    .045       0   528.4      .1       0
Bank Sta=508.7,528.4
XS Rating Curve= 0 ,0
Exp/Cntr=0.3,0.1

Type RM Length L Ch R = 1 ,27778.3 ,300,297.7,295.1
XS GIS Cut Line= 2
     1820053.817      375055.935     1820588.756      375616.916
#Sta/Elev= 30
       0 1242.46      24 1228.89      40 1226.06    67.9  1207.7    91.9 1199.05
   127.9 1171.64   139.8  1168.8   147.8 1164.63   171.8 1143.91   187.8 1140.61
   211.8 1122.12   295.7 1076.55   319.6 1069.88   395.6 1070.57   411.6 1066.59
   423.7  1065.9   435.5 1064.51   443.7 1066.06   459.5 1069.68   515.4 1067.28
   527.4 1068.16   535.4 1070.93   571.4  1098.3   627.3 1132.28   651.3 1148.97
   667.3 1162.35   679.3 1168.86   743.2 1212.42   759.2 1218.99   775.2 1221.24
#Mann= 3 , 0 , 0
       0      .1       0   423.7    .045       0   443.7      .1       0
#XS Ineff= 2 , 0
       0   395.6                       0
Permanent Ineff=
       F       F
Bank Sta=423.7,443.7
XS Rating Curve= 0 ,0
Exp/Cntr=0.3,0.1

Type RM Length L Ch R = 1 ,27480.5 ,475.8,469,461.4
XS GIS Cut Line= 2
     1819895.397      375341.308     1820407.549      375774.251
#Sta/Elev= 30
       0 1177.77    31.9 1158.97    95.8 1115.18   107.8 1112.15   127.7 1102.12
   147.7 1099.07   187.6 1087.31   203.6 1076.93   219.6 1073.93   235.5 1062.18
   267.4 1060.56   299.4  1064.6   331.3 1064.23   348.9 1058.26   363.3 1056.44
   371.2 1057.62   395.2 1063.82   407.2 1062.89   415.2 1065.18   431.1 1079.98
     471 1109.05     491 1114.27     507 1123.24   526.9 1140.74   578.8 1176.62
   594.8  1183.5   626.7 1205.26   638.7 1209.12   654.7 1210.62   670.6 1219.61
#Mann= 3 , 0 , 0
       0      .1       0   348.9    .045       0   371.2      .1       0
#XS Ineff= 2 , 0
       0   323.3                       0
Permanent Ineff=
       F       F
Bank Sta=348.9,371.2
XS Rating Curve= 0 ,0
Exp/Cntr=0.3,0.1

Type RM Length L Ch R = 1 ,27011.5 ,382.3,389.2,396.3
XS GIS Cut Line= 2
     1819578.556      375774.251     1820171.004      376079.155
#Sta/Elev= 30
       0 1211.64       8 1212.24    43.9 1194.92    91.8 1162.74   103.7  1156.8
   151.6 1120.32   163.6 1108.33   179.5  1104.1   211.5 1083.82   223.4 1072.01
   231.4 1066.03   239.4 1056.59   247.4 1051.32   287.3 1048.09   319.2 1052.42
   359.1 1053.62     379 1049.46     399 1048.02     407 1046.61     421 1047.94
   442.9 1057.93   462.8 1056.28   474.8 1057.88   498.7 1069.48   526.7  1090.5
   542.6 1093.62   558.6 1106.46   598.5 1131.32   638.4 1162.73   666.3 1180.06
#Mann= 3 , 0 , 0
       0      .1       0     399    .045       0     421      .1       0
#XS Ineff= 2 , 0
       0   355.1                       0
Permanent Ineff=
       F       F
Bank Sta=399,421
XS Rating Curve= 0 ,0
Exp/Cntr=0.3,0.1

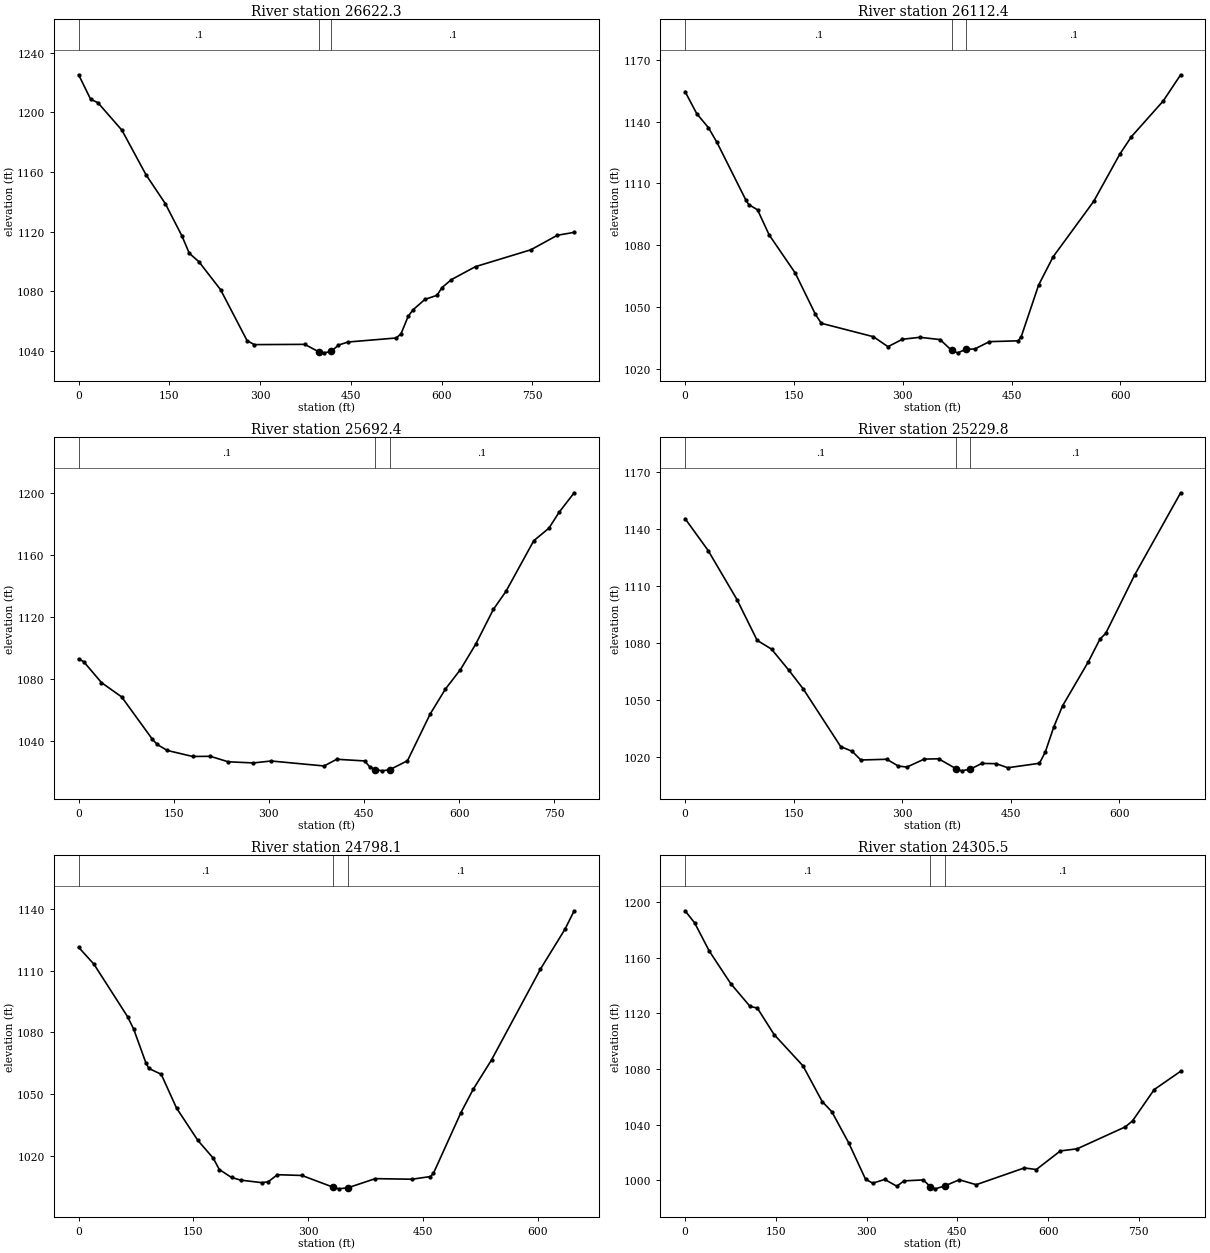
Type RM Length L Ch R = 1 ,26622.3 ,499.8,509.9,520.1
XS GIS Cut Line= 3
     1819418.414      376014.194     1819736.543      376272.255
     1820051.977      376533.427
#Sta/Elev= 30
       0 1225.23    19.9 1208.73    31.8 1206.52    71.6 1187.99   111.4 1158.09
   143.2 1138.78     171 1116.84   182.9  1105.4   198.8 1099.73   234.6 1080.97
   278.4 1046.79   290.3 1044.06   373.8 1044.23   396.6 1039.31   405.7 1038.54
   417.6 1039.47   429.5 1043.76   445.4 1045.81   524.9 1048.51   532.9 1051.24
   544.8  1063.1   552.8 1067.44   572.6 1074.45   592.5 1077.16   600.5 1082.29
   616.4 1087.74   656.1 1096.42   747.6 1107.73   791.3 1117.47   819.2 1119.44
#Mann= 3 , 0 , 0
       0      .1       0   396.6    .045       0   417.6      .1       0
Bank Sta=396.6,417.6
XS Rating Curve= 0 ,0
Exp/Cntr=0.3,0.1

Type RM Length L Ch R = 1 ,26112.4 ,429.7,419.9,409.5
XS GIS Cut Line= 2
     1819211.803      376287.489     1819534.069      376889.702
#Sta/Elev= 30
       0 1154.56      16 1143.89      32 1137.13    43.9 1129.94    83.9 1101.84
    87.9 1099.68    99.9 1097.18   115.8 1085.06   151.8 1066.52   179.7 1046.43
   187.7 1042.14   259.6 1035.61   279.6 1030.78   299.6 1034.38   323.5 1035.33
   351.5 1034.22   367.5 1028.93   375.5 1027.79   387.4  1029.5   399.4 1029.69
   419.4 1033.22   459.3 1033.62   463.3 1035.65   487.3 1060.73   507.3 1074.42
   563.2 1101.32   599.1 1124.18   615.1 1132.67     659 1150.02     683 1162.73
#Mann= 3 , 0 , 0
       0      .1       0   367.5    .045       0   387.4      .1       0
#XS Ineff= 2 , 0
       0   343.5                       0
Permanent Ineff=
       F       F
Bank Sta=367.5,387.4
XS Rating Curve= 0 ,0
Exp/Cntr=0.3,0.1

Type RM Length L Ch R = 1 ,25692.4 ,464.8,462.6,460.2
XS GIS Cut Line= 3
     1818918.834      376494.737     1818879.772      376731.282
     1819301.864      377070.909
#Sta/Elev= 30
       0 1092.96       8 1091.19      36 1077.71    67.9 1068.45   115.9 1041.37
   123.9 1037.78   139.8 1033.93   179.8 1030.04   207.8 1030.14   235.8 1026.61
   275.6 1025.87   303.5 1027.12   387.1 1023.91   407.1 1028.24   450.9 1027.16
   458.8  1023.5   466.8 1021.63   478.8 1020.77   490.7 1021.54   518.6 1027.28
   554.4 1057.43   578.4 1073.52   602.2 1086.13   626.2 1102.46     654 1124.89
     674  1136.6   717.8 1169.24   741.7 1177.31   757.6  1187.5   781.5 1200.15
#Mann= 3 , 0 , 0
       0      .1       0   466.8    .045       0   490.7      .1       0
#XS Ineff= 2 , 0
       0   407.1                       0
Permanent Ineff=
       F       F
Bank Sta=466.8,490.7
XS Rating Curve= 0 ,0
Exp/Cntr=0.3,0.1

Type RM Length L Ch R = 1 ,25229.8 ,437.6,431.7,426.5
XS GIS Cut Line= 2
     1818431.638      376987.359     1818993.704      377379.069
#Sta/Elev= 30
       0 1145.58    31.9 1128.76    71.7 1102.94    99.6 1081.46   119.5 1076.81
   143.4 1065.72   163.3 1055.87   215.1 1025.46     231 1022.97     243 1018.39
   278.8 1018.78   294.8  1015.2   306.7 1014.68   330.6 1018.86   350.5 1019.04
   374.4 1013.84   382.4 1012.68   394.4  1013.6   410.3 1016.59   430.2 1016.45
   446.1 1014.31   489.9 1016.66   497.9 1022.51   509.8 1035.88   521.8  1046.9
   557.6 1070.23   573.6 1082.12   581.5 1085.09   621.4  1115.8   685.1 1159.21
#Mann= 3 , 0 , 0
       0      .1       0   374.4    .045       0   394.4      .1       0
#XS Ineff= 2 , 0
       0   342.6                       0
Permanent Ineff=
       F       F
Bank Sta=374.4,394.4
XS Rating Curve= 0 ,0
Exp/Cntr=0.3,0.1

Type RM Length L Ch R = 1 ,24798.1 ,488.2,492.6,495.9
XS GIS Cut Line= 2
     1818239.581      377415.961     1818821.178      377700.249
#Sta/Elev= 30
       0  1121.5      20 1113.28    63.9 1087.71    71.9 1081.64    87.9 1065.13
    91.9 1062.42   107.9  1059.6   127.9 1043.13   155.8 1027.34   175.8 1018.74
   183.8 1013.16   199.8 1009.28   211.8    1008   239.8 1006.74   247.8 1007.24
   259.7 1010.64   291.7 1010.27     332 1004.62   339.7 1003.75     352 1004.29
   387.6 1008.72   435.6 1008.44   459.6 1009.74   463.5 1011.29   499.5 1040.95
   515.5 1052.29   539.5 1066.65   603.4 1110.93   635.4 1130.33   647.4 1139.31
#Mann= 3 , 0 , 0
       0      .1       0     332    .045       0     352      .1       0
#XS Ineff= 2 , 0
       0   267.7                       0
Permanent Ineff=
       F       F
Bank Sta=332,352
XS Rating Curve= 0 ,0
Exp/Cntr=0.3,0.1

Type RM Length L Ch R = 1 ,24305.5 ,361.9,364.5,367.8
XS GIS Cut Line= 3
     1817983.068      377799.321     1818340.125      377999.833
     1818696.131      378202.192
#Sta/Elev= 30
       0 1193.57    15.9 1184.79    39.8 1164.76    75.5 1141.24   107.4 1124.91
   119.3 1123.79   147.1 1104.75   194.8 1082.27   226.6 1056.64   242.5 1049.35
   270.4 1026.98   298.2 1000.92   310.1  998.05     330 1000.73   349.9  995.87
   361.8   999.7   393.6 1000.39   405.5  995.46   413.5  993.99   429.4  996.13
   453.2 1000.49   481.1  996.96   560.6    1009   580.5 1007.84   620.2  1021.2
     648 1022.73   727.6 1038.48   739.5 1042.79   775.3 1065.24     819 1078.38
#Mann= 3 , 0 , 0
       0      .1       0   405.5    .045       0   429.4      .1       0
#XS Ineff= 2 , 0
       0   393.6                       0
Permanent Ineff=
       F       F
Bank Sta=405.5,429.4
XS Rating Curve= 0 ,0
Exp/Cntr=0.3,0.1

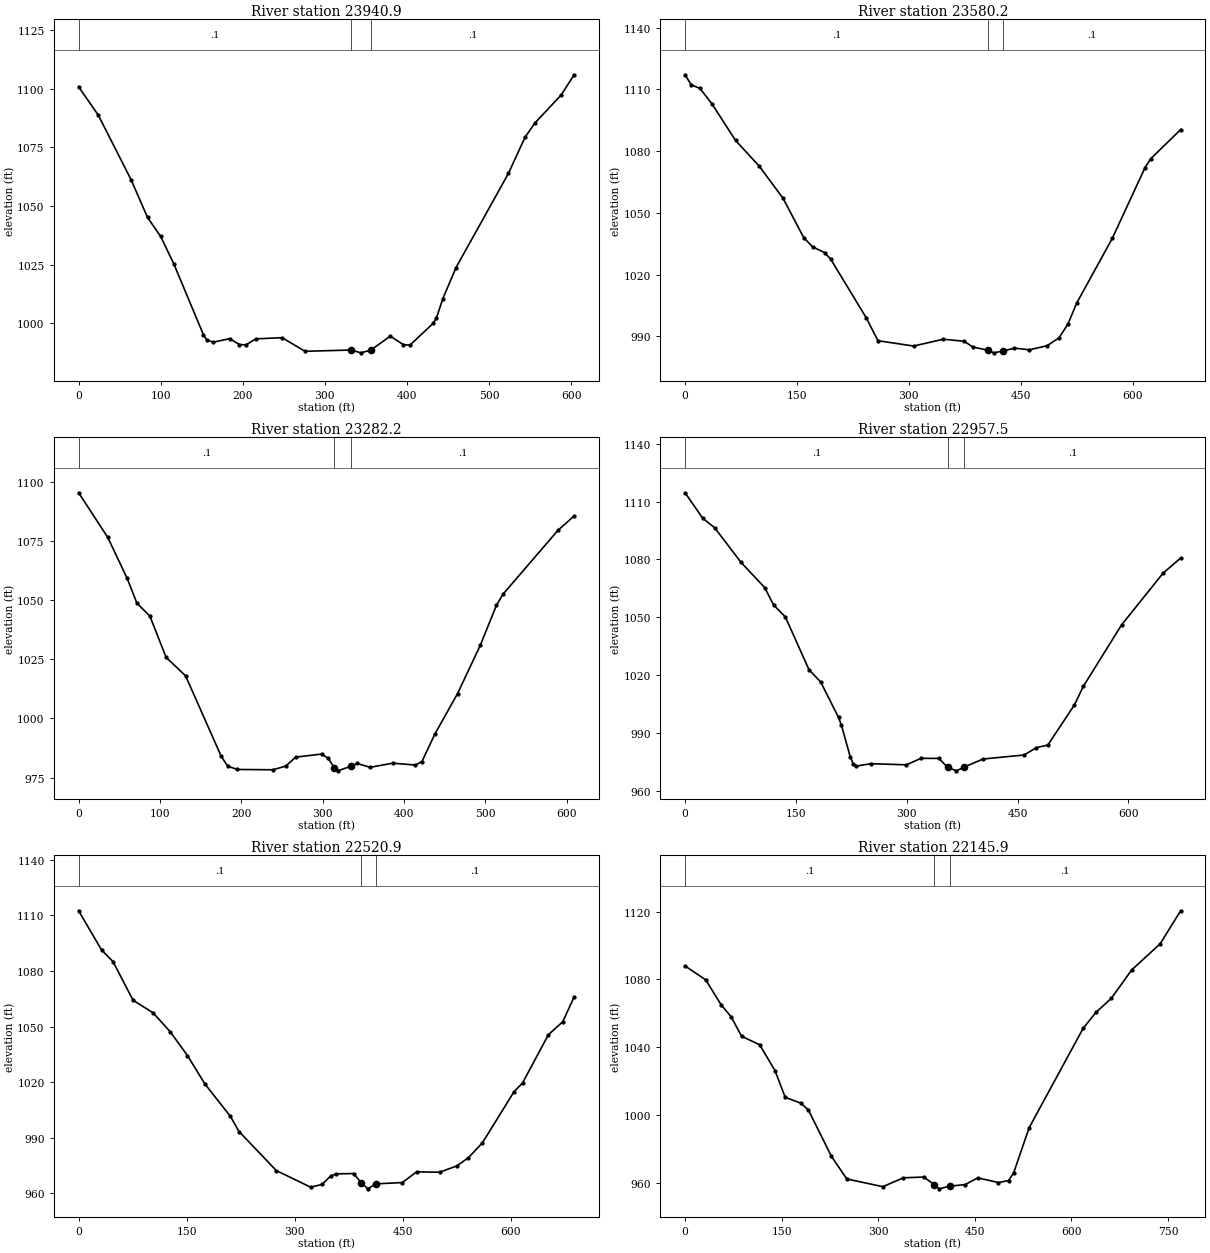
Type RM Length L Ch R = 1 ,23940.9 ,358.2,360.7,361.2
XS GIS Cut Line= 2
     1817954.207      378119.086     1818432.723      378486.925
#Sta/Elev= 30
       0 1100.75      24 1088.66      64  1061.1    83.9 1045.11    99.9 1037.01
   115.9 1025.35   151.9  995.22   155.9  992.96   163.9  991.94   183.9  993.44
   195.9  990.96   203.8  990.79   215.8  993.37   247.8  993.86   275.8  988.07
   331.8  988.61   343.8  987.41   355.7  988.55   379.7  994.52   395.7  990.85
   403.7  990.74   431.7  999.93   435.7 1002.15   443.7 1010.56   459.7 1023.74
   523.6 1063.92   543.6 1079.17   555.6 1085.28   587.6  1097.2   603.6 1105.89
#Mann= 3 , 0 , 0
       0      .1       0   331.8    .045       0   355.7      .1       0
#XS Ineff= 2 ,-1
       0   247.8  993.86   379.7     500  994.52
Permanent Ineff=
       F       F
Bank Sta=331.8,355.7
XS Rating Curve= 0 ,0
Exp/Cntr=0.3,0.1

Type RM Length L Ch R = 1 ,23580.2 ,303.4,298,292.1
XS GIS Cut Line= 2
     1817667.749      378354.546     1818217.879      378726.725
#Sta/Elev= 30
       0 1117.07       8 1112.25    19.9 1110.43    35.8 1103.05    67.6 1085.17
    99.4 1072.65   131.2  1057.1   159.1 1037.88     171 1033.46   186.9 1030.64
   194.9 1027.63   242.6  999.09   258.5  987.85   306.2  985.25     346  988.57
   373.9  987.58   385.8  984.77   405.7  983.24   413.6  981.95   425.6   982.8
   441.5  984.25   461.4  983.42   485.2  985.41   501.1  989.23   513.1   995.9
     525 1006.21   572.7 1037.66   616.5 1071.98   624.4 1076.37   664.2 1090.43
#Mann= 3 , 0 , 0
       0      .1       0   405.7    .045       0   425.6      .1       0
#XS Ineff= 2 , 0
       0     342                       0
Permanent Ineff=
       F       F
Bank Sta=405.7,425.6
XS Rating Curve= 0 ,0
Exp/Cntr=0.3,0.1

Type RM Length L Ch R = 1 ,23282.2 ,327.9,324.6,321
XS GIS Cut Line= 2
     1817545.136      378702.853     1818113.713      378920.952
#Sta/Elev= 30
       0 1095.25    35.8 1076.43    59.7 1059.08    71.6 1048.67    87.6 1043.17
   107.5  1025.8   131.4    1018   175.1  984.15   183.1  979.88     195  978.48
   238.8  978.35   254.7  979.92   266.7  983.69   298.5  984.97   306.5  983.25
   314.4  979.14   318.4   977.9   334.3  979.78   342.3  981.01   358.2  979.39
   386.1  981.12   413.9  980.35   421.9   981.8   437.8  993.42   465.7 1010.53
   493.6 1030.86   513.4 1047.69   521.4  1052.4   589.1 1079.41     609 1085.48
#Mann= 3 , 0 , 0
       0      .1       0   314.4    .045       0   334.3      .1       0
#XS Ineff= 2 , 0
       0   294.5                       0
Permanent Ineff=
       F       F
Bank Sta=314.4,334.3
XS Rating Curve= 0 ,0
Exp/Cntr=0.3,0.1

Type RM Length L Ch R = 1 ,22957.5 ,440.1,436.6,432.8
XS GIS Cut Line= 2
     1817395.397      379029.459     1818045.353       379194.39
#Sta/Elev= 30
       0 1114.62      24 1101.32    39.9 1096.52    75.8 1078.44   107.8 1065.37
   119.7 1056.41   135.7 1050.16   167.6 1022.83   183.6 1016.33   207.6  998.01
   211.5  994.05   223.5  977.51   227.5  973.94   231.5  972.72   251.5  973.99
   299.4  973.39   319.3  976.77   343.3  976.73   355.2  972.14   367.2  970.27
   378.1  972.27   403.1   976.4     459  978.51     475  982.26   490.9  983.68
   526.9 1004.51   538.8 1014.06   590.7 1046.06   646.6 1072.79   670.6 1080.73
#Mann= 3 , 0 , 0
       0      .1       0   355.2    .045       0   378.1      .1       0
#XS Ineff= 2 , 0
       0   339.3             403       0
Permanent Ineff=
       F       F
Bank Sta=355.2,378.1
XS Rating Curve= 0 ,0
Exp/Cntr=0.3,0.1

Type RM Length L Ch R = 1 ,22520.9 ,370,375,380
XS GIS Cut Line= 2
     1817246.742      379505.805     1817932.506      379565.484
#Sta/Elev= 30
       0 1112.46    31.8 1091.36    47.8 1085.02    75.6 1064.22   103.4 1057.43
   127.3 1047.17   151.2 1034.37   175.1 1019.21   210.9 1001.53   222.8  993.38
   274.6  972.33   322.3  963.35   338.2  964.84   350.2  969.41   358.1  970.54
     382  970.71   392.5  965.77   401.9  962.46   412.5  965.14   449.6  965.84
   469.5  971.62   501.4  971.42   525.2  974.79   541.1   979.1     561  987.32
   604.8 1014.82   616.7  1019.6   652.6 1045.62   672.4 1052.54   688.4 1066.02
#Mann= 3 , 0 , 0
       0      .1       0   392.5    .045       0   412.5      .1       0
#XS Ineff= 2 , 0
       0     378                       0
Permanent Ineff=
       F       F
Bank Sta=392.5,412.5
XS Rating Curve= 0 ,0
Exp/Cntr=0.3,0.1

Type RM Length L Ch R = 1 ,22145.9 ,275.8,270.9,265.7
XS GIS Cut Line= 2
     1817191.404      379791.178     1817929.251      380010.362
#Sta/Elev= 30
       0 1087.85    31.9 1079.73    55.8 1065.07    71.8 1057.69    87.7 1046.41
   115.7 1041.39   139.6 1026.14   155.5 1010.34   179.5 1006.94   191.4 1002.94
   227.3  975.49   251.2  962.15   307.1  957.59     339  962.83   370.9  963.28
   386.8  958.85   394.8  956.32   410.8  957.93   434.7  958.79   454.6   962.8
   486.6  960.04   502.5  961.21   510.5  965.93   534.4  992.41   618.2    1051
   638.1 1060.46     662 1068.77   693.9 1085.64   737.8 1100.92   769.7 1120.46
#Mann= 3 , 0 , 0
       0      .1       0   386.8    .045       0   410.8      .1       0
#XS Ineff= 2 , 0
       0   366.9                       0
Permanent Ineff=
       F       F
Bank Sta=386.8,410.8
XS Rating Curve= 0 ,0
Exp/Cntr=0.3,0.1