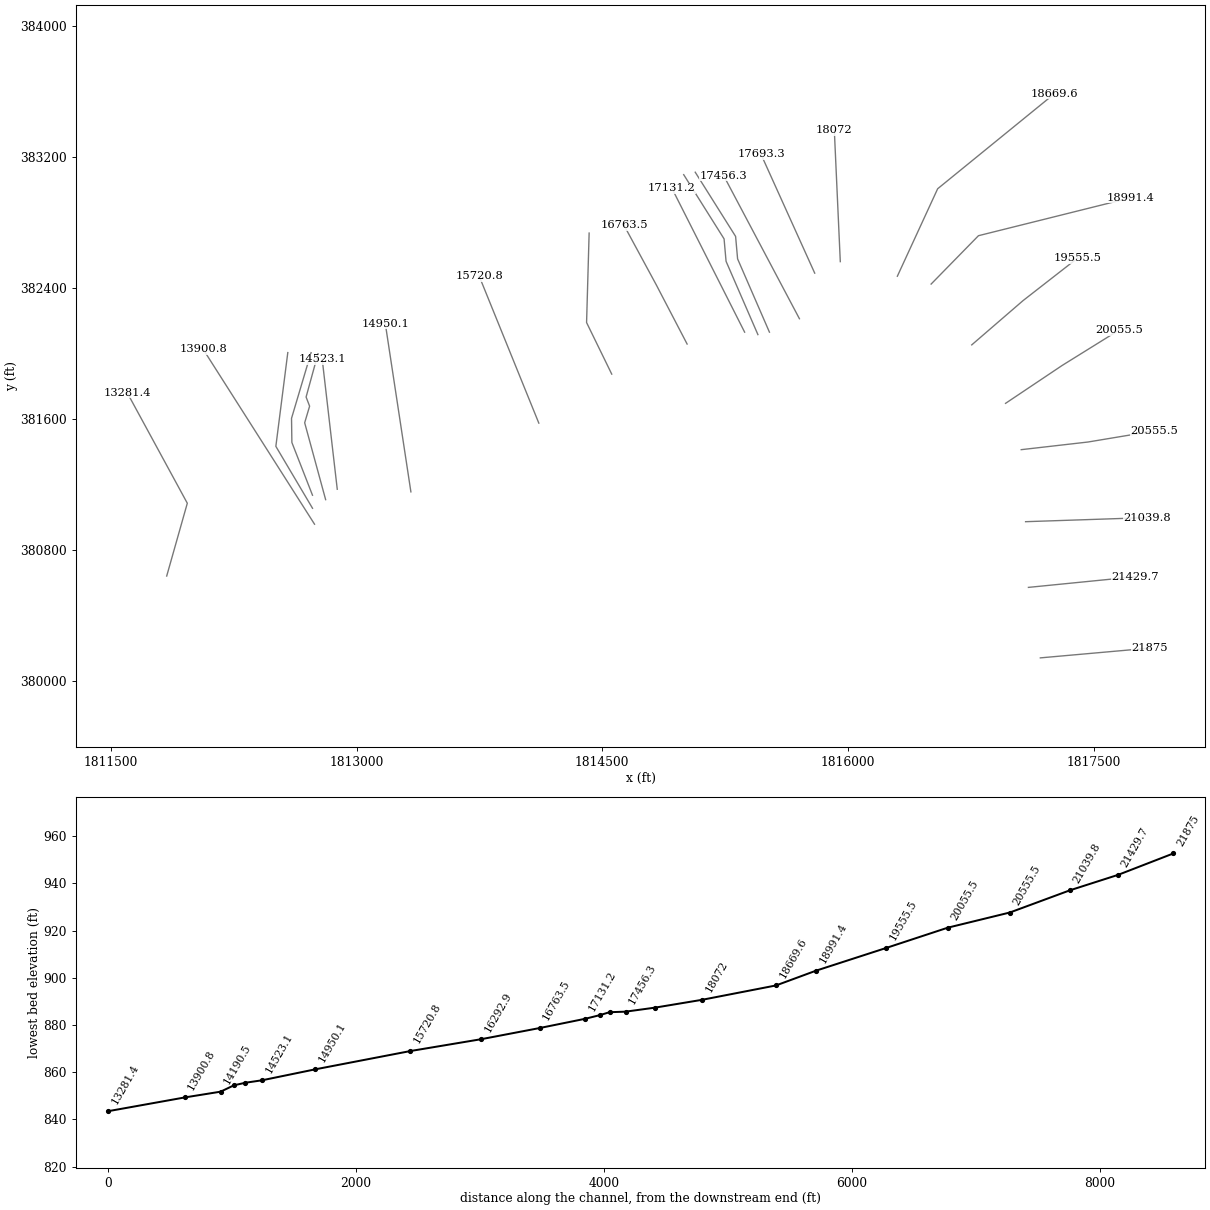
HEC-RAS study WHITEOAKCK.prj: WHITEOAKCK

--- WHITEOAKCK.g01 (geometry) --- (continued)

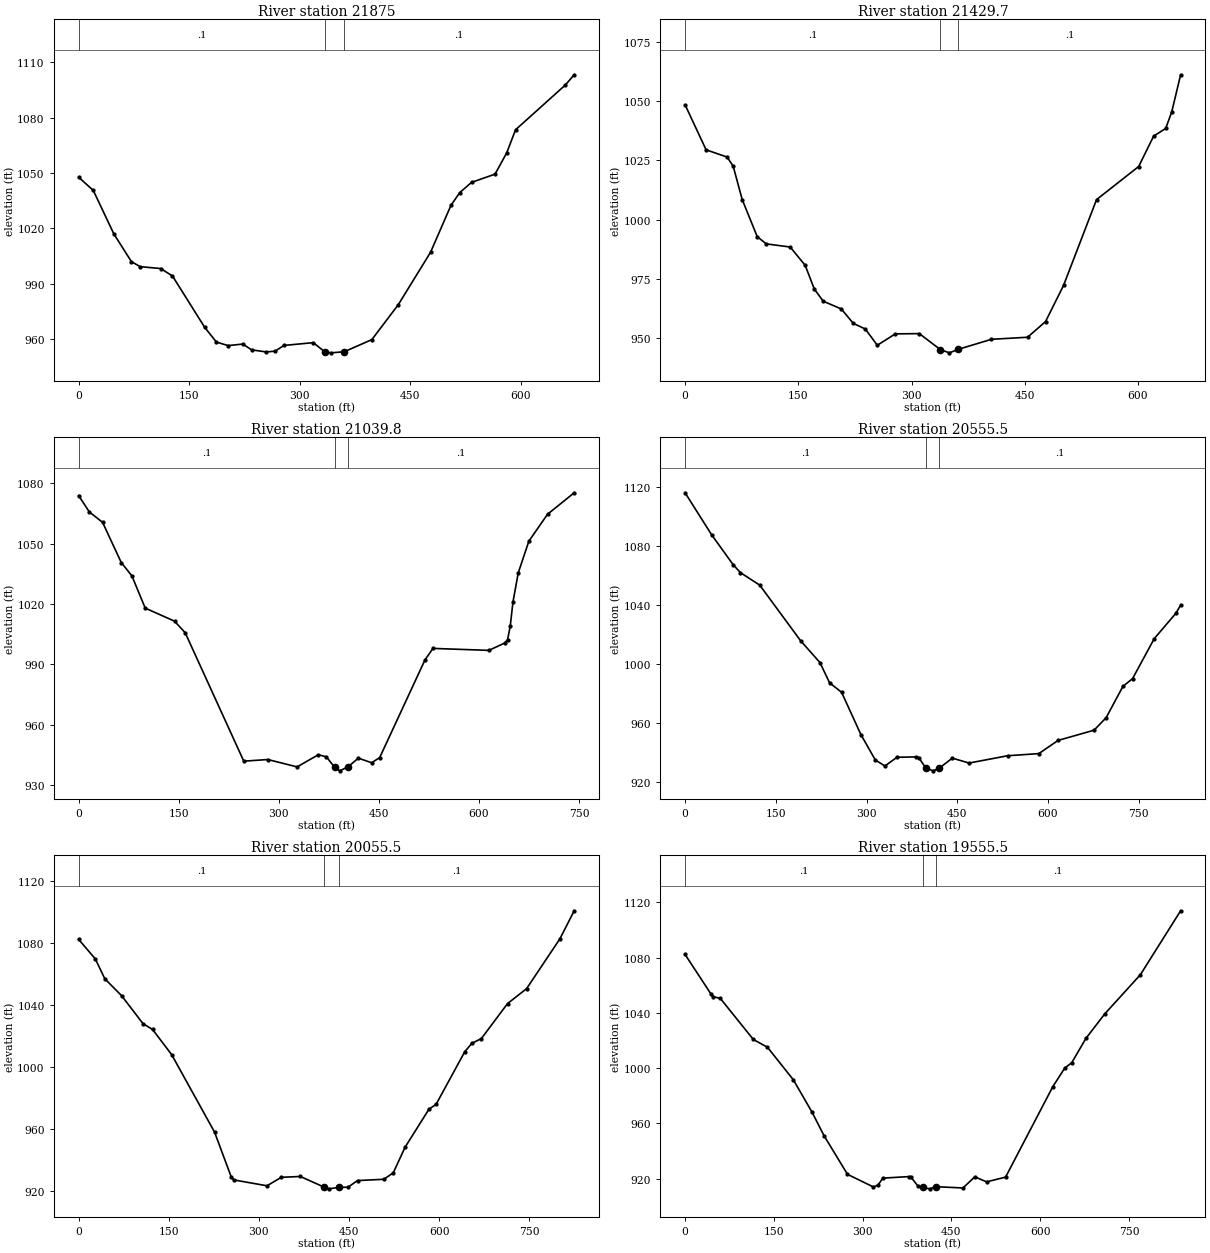
Type RM Length L Ch R = 1 ,21875   ,444.9,445.3,445.4
XS GIS Cut Line= 2
     1817175.128        380138.4     1817844.615      380198.079
#Sta/Elev= 30
       0 1047.74    19.9 1040.58    47.7 1017.12    71.6 1002.07    83.5  999.36
   111.4  998.33   127.3   994.3     171  966.51   186.9  958.55   202.8  956.66
   222.7  957.49   234.6  954.36   254.5  953.22   266.5  953.64   278.4  956.74
   318.2  958.25   334.1  953.19     342  952.74   360.3  953.33   397.7   959.9
   433.5  978.76   477.3 1007.14   505.1 1032.62     517 1039.44   532.9 1044.95
   564.8 1049.41   580.7    1061   592.6  1073.4   660.2 1097.65   672.1 1103.15
#Mann= 3 , 0 , 0
       0      .1       0   334.1    .045       0   360.3      .1       0
#XS Ineff= 2 , 0
       0     318  958.24               0
Permanent Ineff=
       F       F
Bank Sta=334.1,360.3
XS Rating Curve= 0 ,0
Exp/Cntr=0.3,0.1

Type RM Length L Ch R = 1 ,21429.7 ,391.4,389.9,388.2
XS GIS Cut Line= 2
     1817102.428      380569.173      1817755.64      380634.277
#Sta/Elev= 30
       0 1048.48    27.8 1029.47    55.7  1026.4    63.7 1022.55    75.6 1008.47
    95.5   992.8   107.4  989.72   139.2  988.39   159.1  980.64   171.1  970.64
     183  965.48   206.9  962.22   222.8  956.12   238.7  953.74   254.6  946.87
   278.5  951.69   310.3  951.79   338.2  945.02   350.1  943.67     362  945.17
   405.8  949.39   453.6  950.26   477.4  956.86   501.3  972.15     545 1008.42
   600.8 1022.41   620.6 1035.24   636.6  1038.5   644.5 1045.38   656.4 1061.18
#Mann= 3 , 0 , 0
       0      .1       0   338.2    .045       0     362      .1       0
#XS Ineff= 2 , 0
       0     306   951.7               0
Permanent Ineff=
       F       F
Bank Sta=338.2,362
XS Rating Curve= 0 ,0
Exp/Cntr=0.3,0.1

Type RM Length L Ch R = 1 ,21039.8 ,482.1,484.4,487.4
XS GIS Cut Line= 2
     1817085.067      380970.648     1817827.254      380995.605
#Sta/Elev= 30
       0 1073.97      16 1065.85    35.9 1060.65    63.9 1040.66    79.8 1034.05
    99.8 1018.01   143.7 1011.52   159.7 1005.76   247.5  941.91   283.5  942.72
   327.4  939.06   359.3  945.12   371.3  944.05   383.8  938.77   391.3   937.1
   403.8  939.12   419.2  943.41   439.2  941.11   451.2  943.72     519  992.24
     531  997.98   614.8     997   638.8  1000.7   642.8 1002.33   646.8 1009.04
   650.8 1020.88   658.8 1035.55   674.7  1051.3   702.7 1064.68   742.6 1075.36
#Mann= 3 , 0 , 0
       0      .1       0   383.8    .045       0   403.8      .1       0
#XS Ineff= 2 , 0
       0   359.3   945.1               0
Permanent Ineff=
       F       F
Bank Sta=383.8,403.8
XS Rating Curve= 0 ,0
Exp/Cntr=0.3,0.1

Type RM Length L Ch R = 1 ,20555.5 ,487.9,500,509.6
XS GIS Cut Line= 3
     1817058.438       381410.82     1817465.889      381457.531
      1817869.71      381524.835
#Sta/Elev= 30
       0 1115.84    43.8 1087.45    79.6 1067.12    91.6 1061.78   123.4 1053.37
   191.1 1015.69     223 1000.97   238.9  987.26   258.8  980.84   290.7  952.24
   314.6  935.02   330.5  930.96   350.4  936.88   382.2  937.12   386.2   936.7
   398.2  929.57   410.1  927.69   420.1  929.42   441.9  936.29   469.7  932.96
   533.3   937.9     585  939.35   616.8  948.27   676.4  955.21   696.3  963.66
   724.1  984.88     740  990.09   775.8 1017.11   811.6 1034.28   819.5  1039.8
#Mann= 3 , 0 , 0
       0      .1       0   398.2    .045       0   420.1      .1       0
#XS Ineff= 2 , 0
       0   382.2   937.1               0
Permanent Ineff=
       F       F
Bank Sta=398.2,420.1
XS Rating Curve= 0 ,0
Exp/Cntr=0.3,0.1

Type RM Length L Ch R = 1 ,20055.5 ,495.6,500,502.3
XS GIS Cut Line= 3
     1816962.739      381693.924     1817308.871      381925.804
      1817655.44      382141.314
#Sta/Elev= 30
       0 1082.09    27.8 1069.44    43.6 1056.65    71.4 1045.82   107.1 1027.76
     123 1024.01   154.8 1007.79   226.2  957.84   253.9     929   257.9  927.04
   313.5  923.24   337.3   928.7     369  929.24   408.7  922.34   416.6  921.27
   432.5   922.2   448.3  922.33   464.2  926.61   507.8  927.42   523.6  931.57
   543.4  948.18     583  972.58   594.9  975.75   642.5 1009.57   654.4 1015.08
   670.2  1018.1   713.8 1040.68   745.5  1050.3     801 1082.44   824.7  1100.5
#Mann= 3 , 0 , 0
       0      .1       0   408.7    .045       0   432.5      .1       0
#XS Ineff= 2 , 0
       0     369  929.24               0
Permanent Ineff=
       F       F
Bank Sta=408.7,432.5
XS Rating Curve= 0 ,0
Exp/Cntr=0.3,0.1

Type RM Length L Ch R = 1 ,19555.5 ,557.7,564.1,567.9
XS GIS Cut Line= 3
     1816756.266       382051.22     1817069.248      382321.518
     1817403.443      382582.042
#Sta/Elev= 30
       0 1082.29    43.7 1053.69    47.7 1051.79    59.6 1050.45   115.3 1020.76
   139.2 1015.11   182.9  991.57   214.7  967.97   234.6  951.21   274.4  923.12
   318.1     914   326.1  915.33     334  920.37   377.8  921.48   381.7  921.07
   393.7  914.45   401.6  913.59   413.5  912.62   423.5  914.18   469.5  913.25
   489.5  921.31   509.5  917.66   541.5   921.1   621.4  986.66   641.4 1000.02
   653.4    1004   677.4 1021.65   709.4 1039.44   769.3 1067.66   837.3 1113.94
#Mann= 3 , 0 , 0
       0      .1       0   401.6    .045       0   423.5      .1       0
#XS Ineff= 2 , 0
       0   373.8   920.9               0
Permanent Ineff=
       F       F
Bank Sta=401.6,423.5
XS Rating Curve= 0 ,0
Exp/Cntr=0.3,0.1

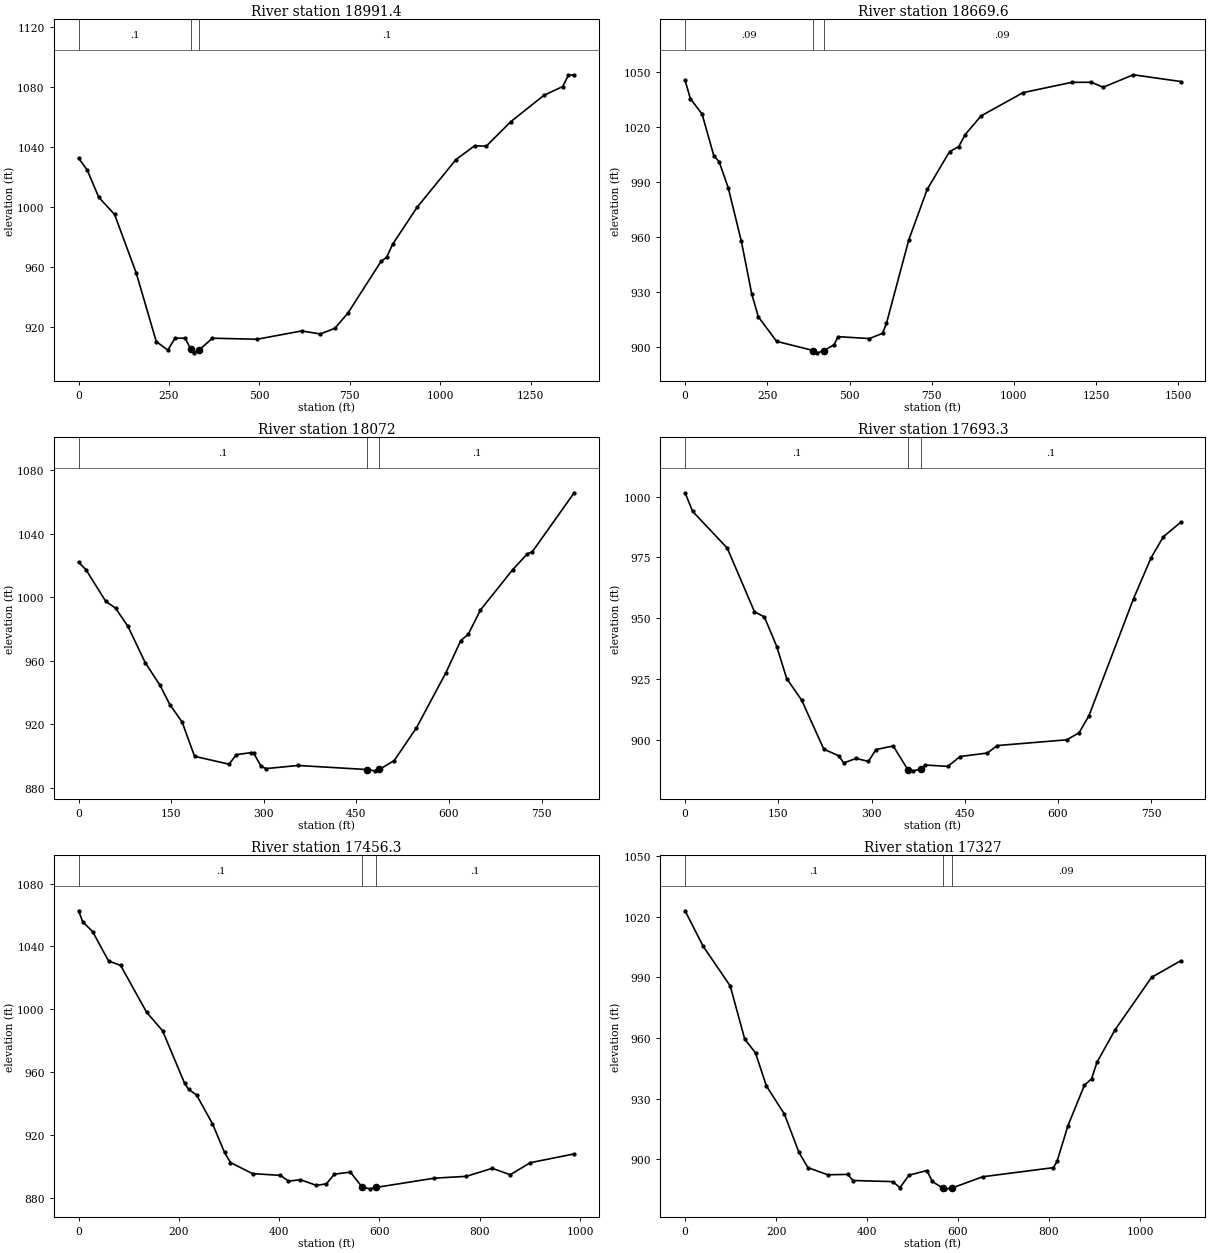
Type RM Length L Ch R = 1 ,18991.4 ,313.1,321.8,330.3
XS GIS Cut Line= 3
     1816508.121       382422.84     1816797.183      382718.413
     1817725.511      382949.967
#Sta/Elev= 30
       0 1032.51    23.8 1024.64    55.6 1006.53    99.4  995.07     159  956.33
   214.7  910.55   246.5  904.81   266.3   912.7   294.2  912.82   310.1  905.48
     318  903.02   333.9  904.97   369.7  912.76   493.2  912.06   616.7  917.59
   668.6  915.58   708.4  919.36   744.3  929.36     836   963.8   851.9  966.67
   867.9  975.13   935.7  999.79  1043.3 1031.57  1095.1 1040.81    1127 1040.51
  1194.8 1056.78  1286.5 1074.34  1338.3 1080.16  1354.2  1087.7  1370.2 1088.01
#Mann= 3 , 0 , 0
       0      .1       0   310.1    .045       0   333.9      .1       0
#XS Ineff= 2 , 0
       0     290   912.4               0
Permanent Ineff=
       F       F
Bank Sta=310.1,333.9
XS Rating Curve= 0 ,0
Exp/Cntr=0.3,0.1

Type RM Length L Ch R = 1 ,18669.6 ,583.1,597.6,609.4
XS GIS Cut Line= 3
       1816301.9        382470.8     1816548.052      383005.306
     1817260.233      383585.384
#Sta/Elev= 30
       0 1045.38    15.9  1035.5    51.7 1026.94    87.5  1004.2   103.4 1001.08
   131.2   986.8     171   957.7   202.8  928.82   222.7  916.43   278.3  903.04
   389.7  898.04   401.6  896.78   421.5  897.84   453.3  901.26   465.2   905.6
   560.6  904.57   600.4  907.41   612.4  912.85   680.3  958.41   736.2  985.92
   804.1 1006.48   832.1 1009.27     852 1015.85     900    1026  1027.8  1038.7
  1175.5 1044.31  1235.4 1044.36  1271.4 1041.66  1363.2 1048.44    1507 1044.77
#Mann= 3 , 0 , 0
       0     .09       0   389.7    .045       0   421.5     .09       0
Bank Sta=389.7,421.5
XS Rating Curve= 0 ,0
Exp/Cntr=0.3,0.1

Type RM Length L Ch R = 1 ,18072   ,367.9,378.7,390
XS GIS Cut Line= 2
     1815953.433      382559.993     1815916.975      383362.076
#Sta/Elev= 30
       0 1021.93      12 1017.21    43.9  997.36    59.9  993.07    79.9  981.58
   107.8  958.85   131.8  944.52   147.8  932.39   167.8  921.28   187.8  899.83
   243.7  894.86   255.6  900.88   279.6  902.15   283.6  901.83   295.6  893.56
   303.6  892.08   355.5  894.06   466.7  891.51   479.4  890.68   487.3  891.55
   511.3  897.13   547.3  917.71   595.2  952.53   619.2  972.69   631.1  976.53
   651.1  991.91     703 1017.16     727 1027.26     735 1028.52   802.9 1065.68
#Mann= 3 , 0 , 0
       0      .1       0   466.7    .045       0   487.3      .1       0
#XS Ineff= 2 , 0
       0   283.6                       0
Permanent Ineff=
       F       F
Bank Sta=466.7,487.3
XS Rating Curve= 0 ,0
Exp/Cntr=0.3,0.1

Type RM Length L Ch R = 1 ,17693.3 ,235.4,236.9,238.5
XS GIS Cut Line= 2
     1815797.183      382489.681     1815469.058      383216.243
#Sta/Elev= 30
       0 1001.56      12  993.95    67.8  978.85   111.6  952.71   127.6  950.56
   147.5   938.4   163.4  925.27   187.4  916.46   223.2  896.26   247.1  893.57
   255.1  890.62     275  892.45     295  891.24   306.9  896.08   334.8  897.59
   358.8  887.66   366.7  887.37   379.2  888.03   386.6  889.76   422.5  889.19
   442.5  893.25   486.3  894.69   502.2  897.75   613.9  900.11   633.8     903
   649.7  910.01   721.5  958.13   749.4  974.73   769.3  983.48   797.2  989.42
#Mann= 3 , 0 , 0
       0      .1       0   358.8    .045       0   379.2      .1       0
#XS Ineff= 2 , 0
       0   330.8                       0
Permanent Ineff=
       F       F
Bank Sta=358.8,379.2
XS Rating Curve= 0 ,0
Exp/Cntr=0.3,0.1

Type RM Length L Ch R = 1 ,17456.3 ,139.5,129.3,118.2
XS GIS Cut Line= 2
      1815703.81      382211.035      1815241.57      383084.733
#Sta/Elev= 30
       0 1062.72       8 1055.76    27.9 1049.45    59.8  1030.7    83.7 1027.96
   135.5  998.13   167.4  986.34   211.2     953   219.2  949.02   235.2  945.45
     267  927.07     291  908.86   302.9  902.41   346.8  895.36   402.6  894.24
   418.5   890.6   442.4  891.46   474.3  887.88   494.2  888.85   510.2  895.03
     542  896.31     566   886.6   581.9  885.67   593.9  886.61   709.4  892.46
   773.2  893.63     825  898.74   860.9  894.63   900.8  902.32   988.4  907.91
#Mann= 3 , 0 , 0
       0      .1       0     566    .045       0   593.9      .1       0
#XS Ineff= 2 , 0
       0   538.1                       0
Permanent Ineff=
       F       F
Bank Sta=566,593.9
XS Rating Curve= 0 ,0
Exp/Cntr=0.3,0.1

Type RM Length L Ch R = 1 ,17327   ,78.4,78,78.4
XS GIS Cut Line= 4
      1815520.65      382129.004     1815326.205       382576.92
     1815314.053      382714.073     1815067.525      383106.434
#Sta/Elev= 30
       0  1022.9    39.7 1005.34    99.2  985.75     131  959.51   154.8  952.63
   178.6  936.37   218.4  922.35   250.1  903.55     270  895.92   313.6   892.4
   357.3  892.57   369.2  889.56   456.5  889.01   472.4  886.03   492.2  892.19
   531.6   894.5   543.4  889.08     567  885.74   570.9  885.44   586.6  885.83
     654  891.41   809.8  895.92   817.7  899.02   841.7   916.7   877.7  936.56
   893.6  939.88   905.6  948.05   945.6   964.2  1025.5  989.99  1089.4  998.16
#Mann= 3 , 0 , 0
       0      .1       0     567    .045       0   586.6     .09       0
#XS Ineff= 2 , 0
       0   527.6                       0
Permanent Ineff=
       F       F
Bank Sta=567,586.6
XS Rating Curve= 0 ,0
Exp/Cntr=0.3,0.1

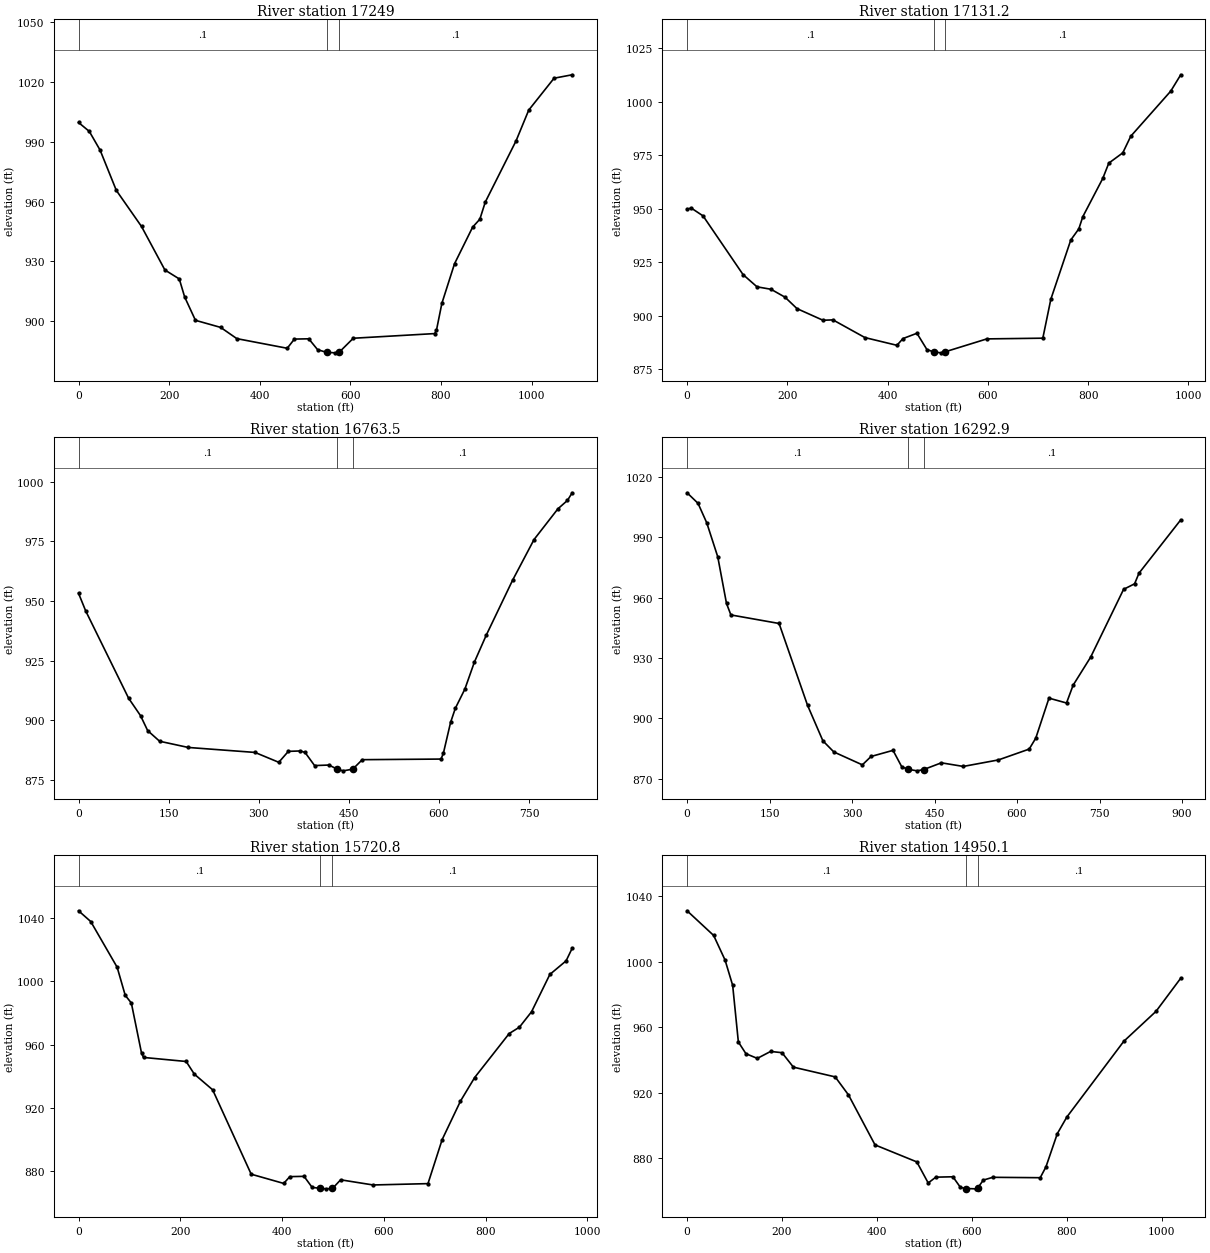
Type RM Length L Ch R = 1 ,17249   ,107.7,117.8,128
XS GIS Cut Line= 4
     1815450.251      382113.986     1815255.806      382561.903
     1815243.653      382699.056     1814997.126      383091.417
#Sta/Elev= 30
       0  999.57    23.8   995.1    47.6  985.72    83.4  965.55     139  947.48
   190.6  925.69   222.3  921.22   234.2  912.17     258  900.49   313.6  896.94
   349.4  891.31   460.5  886.49   476.4  891.09     508  891.23   527.6  885.78
   547.3  884.45     567   884.2   574.8  884.41   606.3  891.51   785.8  893.84
   789.8  895.44   801.8  908.98   829.7  928.81   869.7  947.16   885.6  951.13
   897.6  959.71   965.5  990.36   993.5 1005.78  1049.4 1021.75  1089.4 1023.47
#Mann= 3 , 0 , 0
       0      .1       0   547.3    .045       0   574.8      .1       0
#XS Ineff= 2 , 0
       0     508                       0
Permanent Ineff=
       F       F
Bank Sta=547.3,574.8
XS Rating Curve= 0 ,0
Exp/Cntr=0.3,0.1

Type RM Length L Ch R = 1 ,17131.2 ,366.9,367.7,368.4
XS GIS Cut Line= 2
     1815369.174      382129.004     1814925.164       383007.91
#Sta/Elev= 30
       0   949.7       8  950.39    31.9  946.68   111.6  919.26   139.5  913.52
   167.4  912.38   195.3  908.69   219.3  903.33   271.1  897.89     291  898.07
   354.8  889.79   418.6  886.18   430.6  889.33   458.5  891.81   478.4   884.2
   491.9  883.08   506.3  882.66   514.3  883.11     598  889.18   709.6  889.51
   725.6  907.73   765.4  935.42   781.4  940.62   789.4  946.33   829.2   964.2
   841.2  971.35   869.1  976.16     885  983.92   964.8 1005.02   984.7 1012.66
#Mann= 3 , 0 , 0
       0      .1       0   491.9    .045       0   514.3      .1       0
#XS Ineff= 2 , 0
       0   458.5             620       0
Permanent Ineff=
       F       F
Bank Sta=491.9,514.3
XS Rating Curve= 0 ,0
Exp/Cntr=0.3,0.1

Type RM Length L Ch R = 1 ,16763.5 ,483.6,470.6,457.5
XS GIS Cut Line= 3
     1815017.922      382056.392     1814829.046      382419.032
      1814632.45      382782.264
#Sta/Elev= 30
       0  953.19    11.9  945.81    83.4  909.17   103.2  901.88   115.1   895.6
     135  891.14   182.6  888.54   293.8  886.45   333.4  882.31   349.3   886.9
   369.2  887.07   377.1  886.45     393  880.94   416.8  881.16   431.1   879.4
   440.6  878.73   456.5  879.43   472.4  883.41   603.5  883.67   607.4  886.06
   619.4  899.02   627.3  904.94   643.2     913   659.1  924.36   678.9  935.67
   722.6  958.64   758.4  975.75   798.1  988.61     814  992.15   821.9  995.35
#Mann= 3 , 0 , 0
       0      .1       0   431.1    .045       0   456.5      .1       0
#XS Ineff= 2 , 0
       0   361.2                       0
Permanent Ineff=
       F       F
Bank Sta=431.1,456.5
XS Rating Curve= 0 ,0
Exp/Cntr=0.3,0.1

Type RM Length L Ch R = 1 ,16292.9 ,560.5,572.1,583.8
XS GIS Cut Line= 3
       1814557.6      381872.493     1814403.954      382187.597
     1814419.579      382734.472
#Sta/Elev= 30
       0 1012.02    19.9 1006.79    35.8  997.09    55.8  980.23    71.7  957.07
    79.7  951.39   167.3  947.15   219.1  906.51     247   888.9   266.9  883.38
   318.7  876.98   334.6  881.14   374.5  884.18   390.5  875.96   402.5  874.74
   418.5  874.01   430.4  874.67   462.4  877.99   502.3   876.2   566.2  879.43
   622.1   884.8   634.1  890.24   658.1  910.09     690  907.68     702  916.51
   733.9  930.45   793.8   964.1   813.8  966.84   821.8  972.12   897.7  998.57
#Mann= 3 , 0 , 0
       0      .1       0   402.5    .045       0   430.4      .1       0
#XS Ineff= 2 , 0
       0   370.5                       0
Permanent Ineff=
       F       F
Bank Sta=402.5,430.4
XS Rating Curve= 0 ,0
Exp/Cntr=0.3,0.1

Type RM Length L Ch R = 1 ,15720.8 ,776.9,770.7,764.3
XS GIS Cut Line= 2
     1814112.288      381573.014     1813747.704      382472.319
#Sta/Elev= 30
       0 1044.41      24 1037.62    75.9 1008.78    91.8  991.06   103.8  986.23
   123.8  954.66   127.8  951.88   211.6  949.33   227.6  941.35   263.6  931.47
   339.4  878.22   403.3  872.39   415.3  876.68   443.3  876.86   459.2  869.89
   475.2   869.3   487.2  868.98   499.2   869.2   515.2  874.68     579  871.42
   686.9  872.27   714.8  900.07   750.8  924.33   778.7  939.21   846.6  966.97
   866.6  970.95   890.5  980.69   926.5 1004.25   958.4 1012.81   970.4 1020.77
#Mann= 3 , 0 , 0
       0      .1       0   475.2    .045       0   499.2      .1       0
Bank Sta=475.2,499.2
XS Rating Curve= 0 ,0
Exp/Cntr=0.3,0.1

Type RM Length L Ch R = 1 ,14950.1 ,428.6,427.1,425.9
XS GIS Cut Line= 2
     1813331.038      381152.875     1813174.788      382180.653
#Sta/Elev= 30
       0 1031.03      56 1015.95      80 1000.93      96  985.49     108  950.88
     124  943.72   147.9  940.87   175.9  945.11   199.9  944.35   223.9  935.52
   311.9  929.57   339.9  918.56   395.8  888.03   483.8  877.64   507.8  864.77
   523.8  868.32   559.8  868.56   575.8  862.02   587.8  861.39   607.8  861.19
   611.8   861.6   623.8  866.52   643.7  868.23   743.7  867.99   755.7  874.56
   779.7   894.9   799.7  905.02   919.6  951.28   987.6  969.62  1039.6  989.84
#Mann= 3 , 0 , 0
       0      .1       0   587.8    .045       0   611.8      .1       0
#XS Ineff= 2 , 0
       0                     643       0
Permanent Ineff=
       F       F
Bank Sta=587.8,611.8
XS Rating Curve= 0 ,0
Exp/Cntr=0.3,0.1

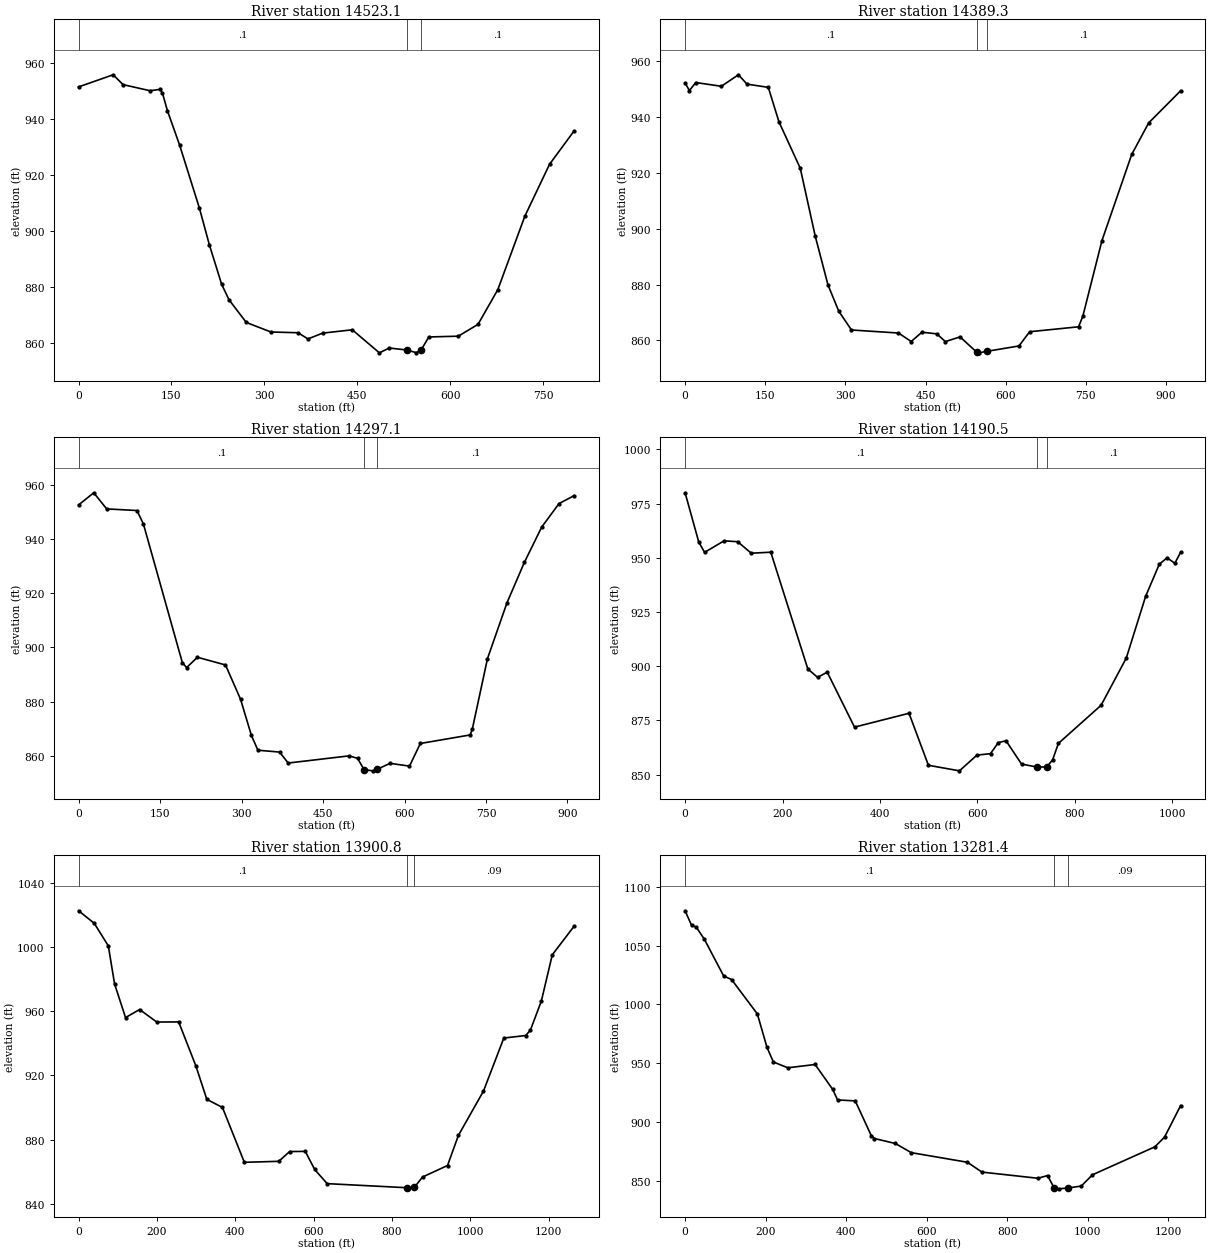
Type RM Length L Ch R = 1 ,14523.1 ,145.9,133.7,122.7
XS GIS Cut Line= 2
     1812881.327      381168.934     1812789.313      381964.073
#Sta/Elev= 30
       0  951.59    55.8  955.91    71.7   952.4   115.5   950.2   131.4  950.71
   135.4  949.36   143.4   943.1   163.3  930.66   195.1  908.26   211.1  895.22
     231  881.05   242.9  875.53   270.8  867.42   310.6  864.02   354.4  863.75
   370.4  861.54   394.2  863.62     442   864.8   485.8  856.57   501.8  858.29
   529.6   857.6   545.6  856.63   553.5  857.66   565.5  862.24   613.3  862.52
   645.1  866.75     677  879.12   720.8  905.43   760.6  923.93   800.4  935.89
#Mann= 3 , 0 , 0
       0      .1       0   529.6    .045       0   553.5      .1       0
Bank Sta=529.6,553.5
XS Rating Curve= 0 ,0
Exp/Cntr=0.3,0.1

Type RM Length L Ch R = 1 ,14389.3 ,89.6,92.3,93.1
XS GIS Cut Line= 5
     1812810.363      381105.349     1812682.325      381575.184
     1812712.477      381676.604     1812691.006      381732.519
     1812763.705      381997.276
#Sta/Elev= 30
       0  952.25       8  949.52      20  952.39    67.9  951.05    99.8  955.17
   115.8  951.82   155.7  950.66   175.6  938.32   215.5  921.67   243.5  897.36
   267.4  879.84   287.4  870.51   311.3  863.73   399.2  862.64   423.1   859.6
   443.1  862.93     471  862.34     487  859.57   514.4  861.26   545.3  855.84
   549.7  855.54   565.3  856.11   624.7     858   644.7   863.1   736.2  864.87
   744.2  868.66     780  895.78   835.7  926.64   867.5  937.95   927.2  949.44
#Mann= 3 , 0 , 0
       0      .1       0   545.3    .045       0   565.3      .1       0
Bank Sta=545.3,565.3
XS Rating Curve= 0 ,0
Exp/Cntr=0.3,0.1

Type RM Length L Ch R = 1 ,14297.1 ,97.7,106.6,112
XS GIS Cut Line= 4
     1812730.068      381132.476       1812604.2      381454.741
      1812602.03      381602.311     1812721.388      382003.787
#Sta/Elev= 30
       0  952.59    27.8  957.07    51.7  951.12   107.4  950.52   119.3  945.54
   190.9  894.42   198.8  892.54   218.7  896.36   270.4  893.52   298.2  880.82
   318.1  867.51   330.1  862.05   369.9  861.37   385.9  857.32   497.6  859.96
   513.5  859.08   525.5  854.89   541.4  854.44   549.4  854.99   573.3   857.2
   609.2  856.19   629.2  864.54   720.9  867.69   724.9  869.86   752.8  895.88
   788.7  916.47   820.7  931.38   852.6  944.41   884.5  953.08   912.4  956.02
#Mann= 3 , 0 , 0
       0      .1       0   525.5    .045       0   549.4      .1       0
Bank Sta=525.5,549.4
XS Rating Curve= 0 ,0
Exp/Cntr=0.3,0.1

Type RM Length L Ch R = 1 ,14190.5 ,277.6,289.7,305.1
XS GIS Cut Line= 3
     1812730.285      381052.615     1812506.327      381431.087
     1812579.244      382004.004
#Sta/Elev= 30
       0  980.01      28  957.34      40  952.52      80  957.85   107.9  957.44
   135.9  952.14   175.9   952.6   251.9  898.79   271.9  894.88   291.8  897.26
   347.8  871.92   459.7  878.31   499.5  854.32   563.2  851.76   599.1  859.01
     627  859.69   642.9  864.75   658.8  865.65   690.7  854.88   722.3  853.52
   742.3  853.54   754.4   856.8   766.4  864.42     854     882   905.8  903.82
   945.6  932.34   973.5  947.07   989.4     950  1005.4  947.52  1017.3  952.57
#Mann= 3 , 0 , 0
       0      .1       0   722.3    .045       0   742.3      .1       0
Bank Sta=722.3,742.3
XS Rating Curve= 0 ,0
Exp/Cntr=0.3,0.1

Type RM Length L Ch R = 1 ,13900.8 ,620.7,619.4,617.8
XS GIS Cut Line= 2
     1812742.496      380955.392     1812063.242      382023.101
#Sta/Elev= 30
       0 1022.59    39.9 1014.78    75.8 1000.73    91.8  976.99   119.8  956.04
   155.7  961.06   199.6  953.25   255.5  953.33   299.4  925.94   327.3   905.1
   367.3  900.02   423.2  865.84     511  866.46   538.9  872.54   578.8  872.66
   602.8  861.39   634.7  852.55   837.7  850.01   842.3  849.31   857.7  850.38
   878.2  856.67   942.1  863.85     970  882.69  1033.9  910.23  1085.8  943.28
  1141.7  944.86  1153.7  948.19  1181.6  966.27  1209.6  995.16  1265.5 1013.01
#Mann= 3 , 0 , 0
       0      .1       0   837.7    .045       0   857.7     .09       0
Bank Sta=837.7,857.7
XS Rating Curve= 0 ,0
Exp/Cntr=0.3,0.1

Type RM Length L Ch R = 1 ,13281.4 ,630.6,623.4,616.4
XS GIS Cut Line= 3
     1811839.718      380638.552     1811965.586      381083.431
     1811598.833      381758.344
#Sta/Elev= 30
       0 1079.51    15.9 1067.23    27.9 1065.54    47.8 1055.36    95.7 1024.21
   115.6 1021.07   179.4  991.97   203.3   963.6   219.2  951.16   255.1  946.23
   322.8  949.02   366.7  927.81   378.6  918.93   422.5  918.14   462.3  888.64
   470.3  886.19     522  881.96   561.8  874.18   701.1  866.03     737  857.69
   876.2  852.45   900.1  854.76     916  844.47     928  843.47   951.9  844.27
   983.7  845.82  1011.6   855.4  1166.8  879.18  1190.7  887.47  1230.5  914.16
#Mann= 3 , 0 , 0
       0      .1       0     916    .045       0   951.9     .09       0
#XS Ineff= 2 , 0
       0     900                       0
Permanent Ineff=
       F       F
Bank Sta=916,951.9
XS Rating Curve= 0 ,0
Exp/Cntr=0.3,0.1