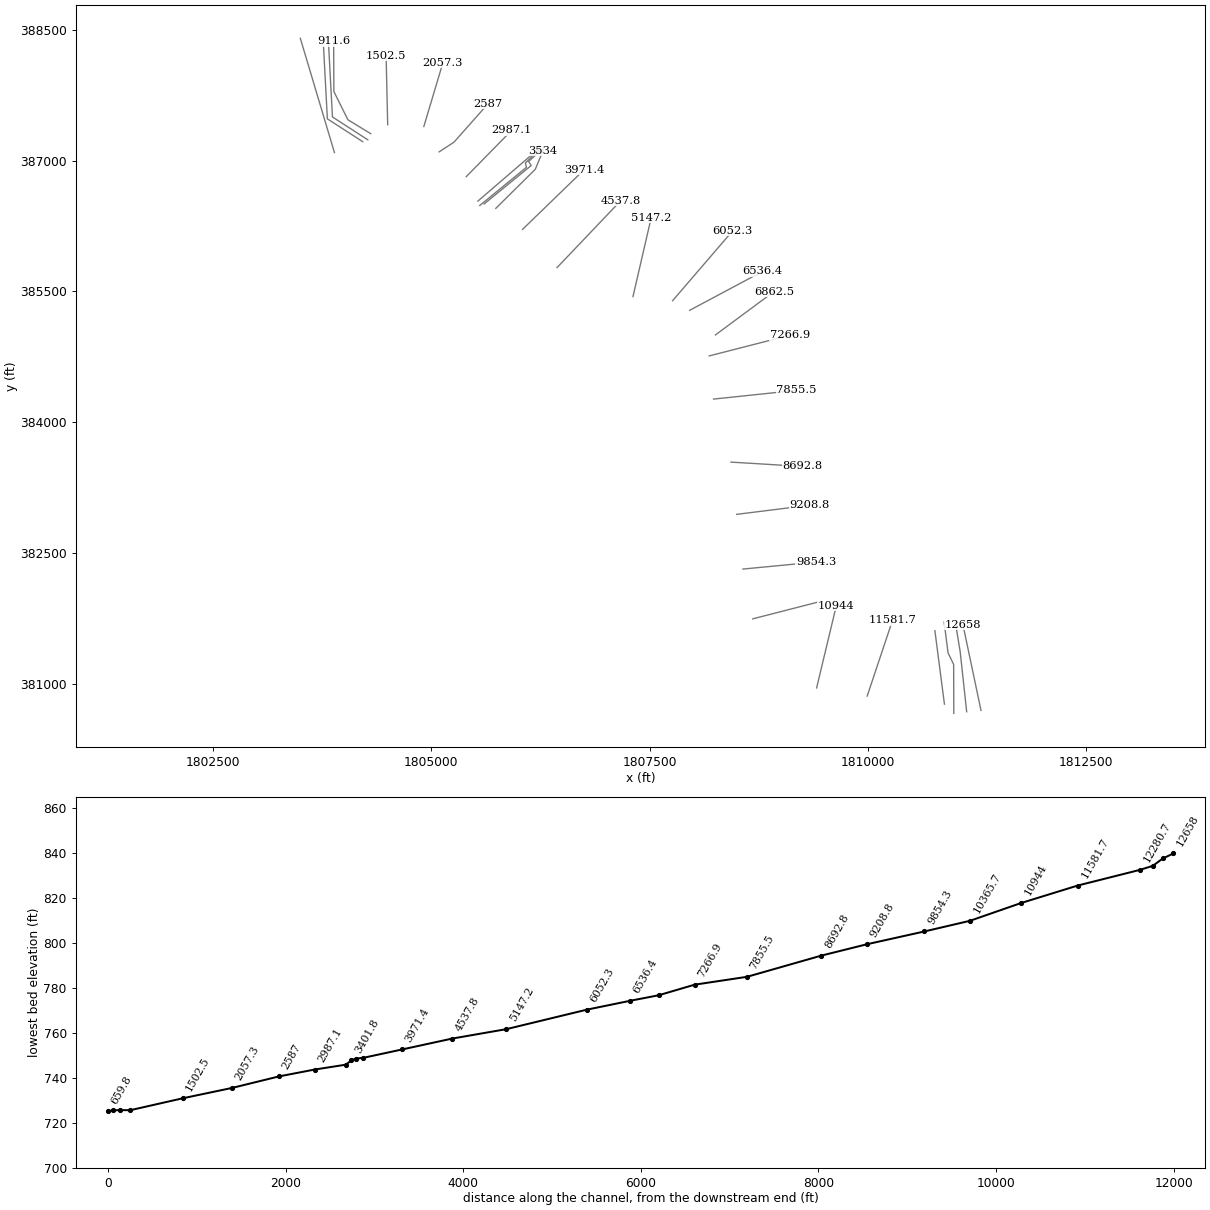
HEC-RAS study WHITEOAKCK.prj: WHITEOAKCK

--- WHITEOAKCK.g01 (geometry) --- (continued)

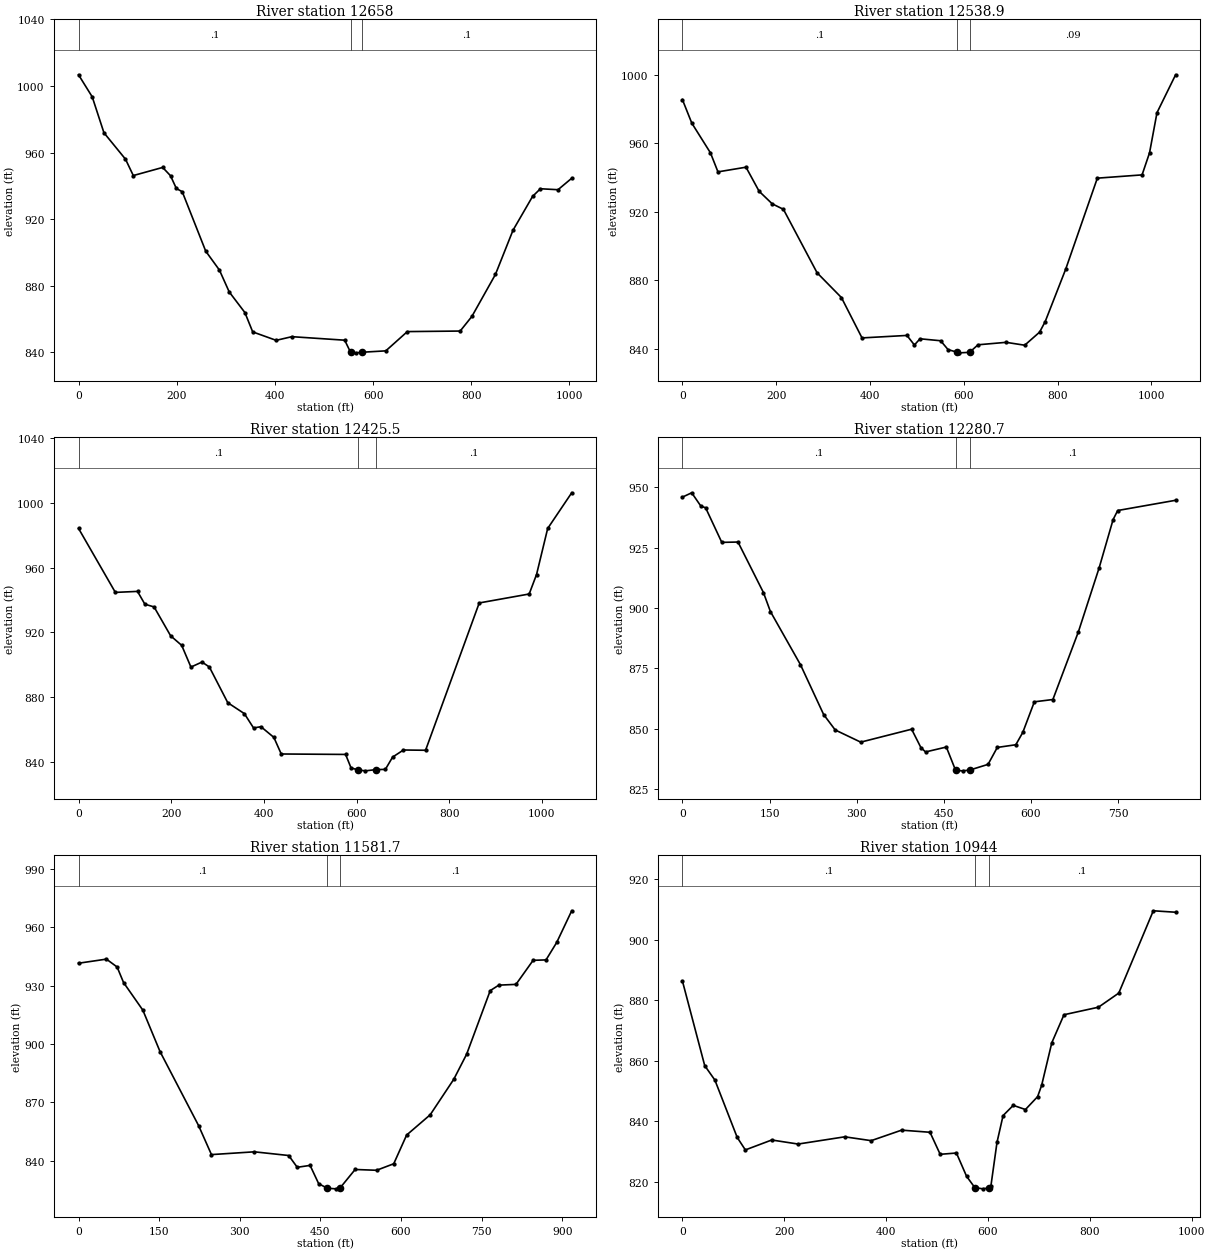
Type RM Length L Ch R = 1 ,12658   ,121.2,119.1,116.9
XS GIS Cut Line= 2
     1811296.909      380695.627     1811089.877        381678.7
#Sta/Elev= 30
       0 1006.67    27.9  993.44    51.8  971.86    95.7  956.01   111.6  946.19
   171.4  951.06   187.4  946.08   199.3  938.42   211.3  936.48   259.1  900.82
     287  889.47     307  876.33   338.9  863.96   354.8  852.36   402.6  847.29
   434.6  849.49   542.2  847.38   554.1  840.13   566.1  839.79   578.1  840.16
   625.9  840.98   669.8  852.54   777.4  852.87   801.3  861.66   849.2  886.83
     885  913.36   924.9  933.68   940.8  938.27   976.7  937.69  1004.6  944.57
#Mann= 3 , 0 , 0
       0      .1       0   554.1    .045       0   578.1      .1       0
Bank Sta=554.1,578.1
XS Rating Curve= 0 ,0
Exp/Cntr=0.3,0.1

Type RM Length L Ch R = 1 ,12538.9 ,105.2,113.4,121.8
XS GIS Cut Line= 3
     1811132.846      380680.002     1811058.627        381366.2
     1811000.468      381722.971
#Sta/Elev= 30
       0  985.35      20  971.63    59.8  954.27    75.8  943.17   135.6   945.9
   163.6  931.84   191.5  924.52   215.4  921.31   287.2  884.26   339.1   869.8
     383  846.25   478.8   847.7   494.7  842.12   506.7  845.74   550.6   844.6
   566.5  839.42   586.5  837.86   590.5  837.54   612.2  837.82   630.4  842.24
   690.2  843.67   729.9  841.99   761.7  849.63   773.6  855.77   817.3  886.36
   884.8   939.5   980.2  941.41   996.1  954.28    1012  977.72  1051.7  999.84
#Mann= 3 , 0 , 0
       0      .1       0   586.5    .045       0   612.2     .09       0
#XS Ineff= 2 , 0
       0   510.7             690       0
Permanent Ineff=
       F       F
Bank Sta=586.5,612.2
XS Rating Curve= 0 ,0
Exp/Cntr=0.3,0.1

Type RM Length L Ch R = 1 ,12425.5 ,153.1,144.8,136.5
XS GIS Cut Line= 4
     1810985.277      380661.512     1810983.541      381222.276
     1810919.304      381355.957     1810874.166      381708.387
#Sta/Elev= 30
       0   984.3    79.5  944.69   127.3  945.31   143.2  937.39   163.1  935.69
   198.8  917.83   222.7   911.9   242.6  898.47   266.5  901.59   282.4  898.52
   322.1  876.43   357.9  869.67   377.8  860.79   393.7  861.58   421.6  854.96
   437.5  844.69   576.4  844.41   588.1  836.12   603.7  834.76   619.3  834.26
   642.7  835.04   662.2  835.15   677.9  842.78   701.3  847.16     749  846.99
   864.8  938.16   972.6   943.7   988.5  955.75  1012.5  984.24  1064.4 1006.34
#Mann= 3 , 0 , 0
       0      .1       0   603.7    .045       0   642.7      .1       0
Bank Sta=603.7,642.7
XS Rating Curve= 0 ,0
Exp/Cntr=0.3,0.1

Type RM Length L Ch R = 1 ,12280.7 ,710,699,687.3
XS GIS Cut Line= 2
     1810878.072      380767.241     1810768.697      381609.255
#Sta/Elev= 30
       0  945.89      16  947.69    31.9  942.12    39.9   941.5    67.8  927.14
    95.7  927.28   139.5  906.35   151.5  898.49   203.3  876.43   243.2  855.78
   263.1   849.4     307  844.36   394.6  849.72   410.6   842.1   418.6   840.3
   454.4  842.33   470.4  832.63   482.4  832.47   494.3  832.77   526.2  835.15
   542.1  842.17     574  843.28     586  848.39   605.9  861.07   637.8  862.02
   681.7  890.06   717.5  916.62   741.5  936.59   749.4  940.34   849.1  944.58
#Mann= 3 , 0 , 0
       0      .1       0   470.4    .045       0   494.3      .1       0
Bank Sta=470.4,494.3
XS Rating Curve= 0 ,0
Exp/Cntr=0.3,0.1

Type RM Length L Ch R = 1 ,11581.7 ,635.5,637.7,639.8
XS GIS Cut Line= 2
      1809992.93      380859.906     1810283.729      381730.132
#Sta/Elev= 30
       0  941.47    51.9  943.58    71.8  939.53    83.8  931.54   119.7  917.34
   151.6  896.09   223.4     858   247.3  843.11   327.1  844.54     391  842.64
   406.9  836.58   430.8  837.56   446.8  828.14   462.8  825.83   478.7  825.51
   486.7  826.02   514.6  835.46   554.5  835.05   586.4   838.4   610.4  853.16
   654.2  863.56   698.1  881.82     722   894.7   765.9  927.39   781.9  930.21
   813.8   930.6   845.7  942.97   869.7  943.18   889.6  952.16   917.5  968.43
#Mann= 3 , 0 , 0
       0      .1       0   462.8    .045       0   486.7      .1       0
Bank Sta=462.8,486.7
XS Rating Curve= 0 ,0
Exp/Cntr=0.3,0.1

Type RM Length L Ch R = 1 ,10944   ,605.4,578.3,550.7
XS GIS Cut Line= 2
     1809413.503      380953.222     1809639.197      381895.063
#Sta/Elev= 30
       0  886.38    43.8  858.43    63.8  853.65   107.6  834.72   123.6  830.59
   175.4  833.87   227.2  832.53   318.8  834.92   370.7  833.65   430.4  837.12
   486.2  836.42   506.2  829.14   538.1  829.57     558  821.89   574.1  818.17
   589.9  817.74   601.8  818.06   605.8  818.69   617.8  833.13   629.7  841.93
   649.7  845.31   673.6  843.93   697.5  848.18   705.4   851.9   725.4  865.99
   749.3  875.23     817  877.72   856.9  882.38   924.7  909.56   968.5  909.08
#Mann= 3 , 0 , 0
       0      .1       0   574.1    .045       0   601.8      .1       0
Bank Sta=574.1,601.8
XS Rating Curve= 0 ,0
Exp/Cntr=0.3,0.1

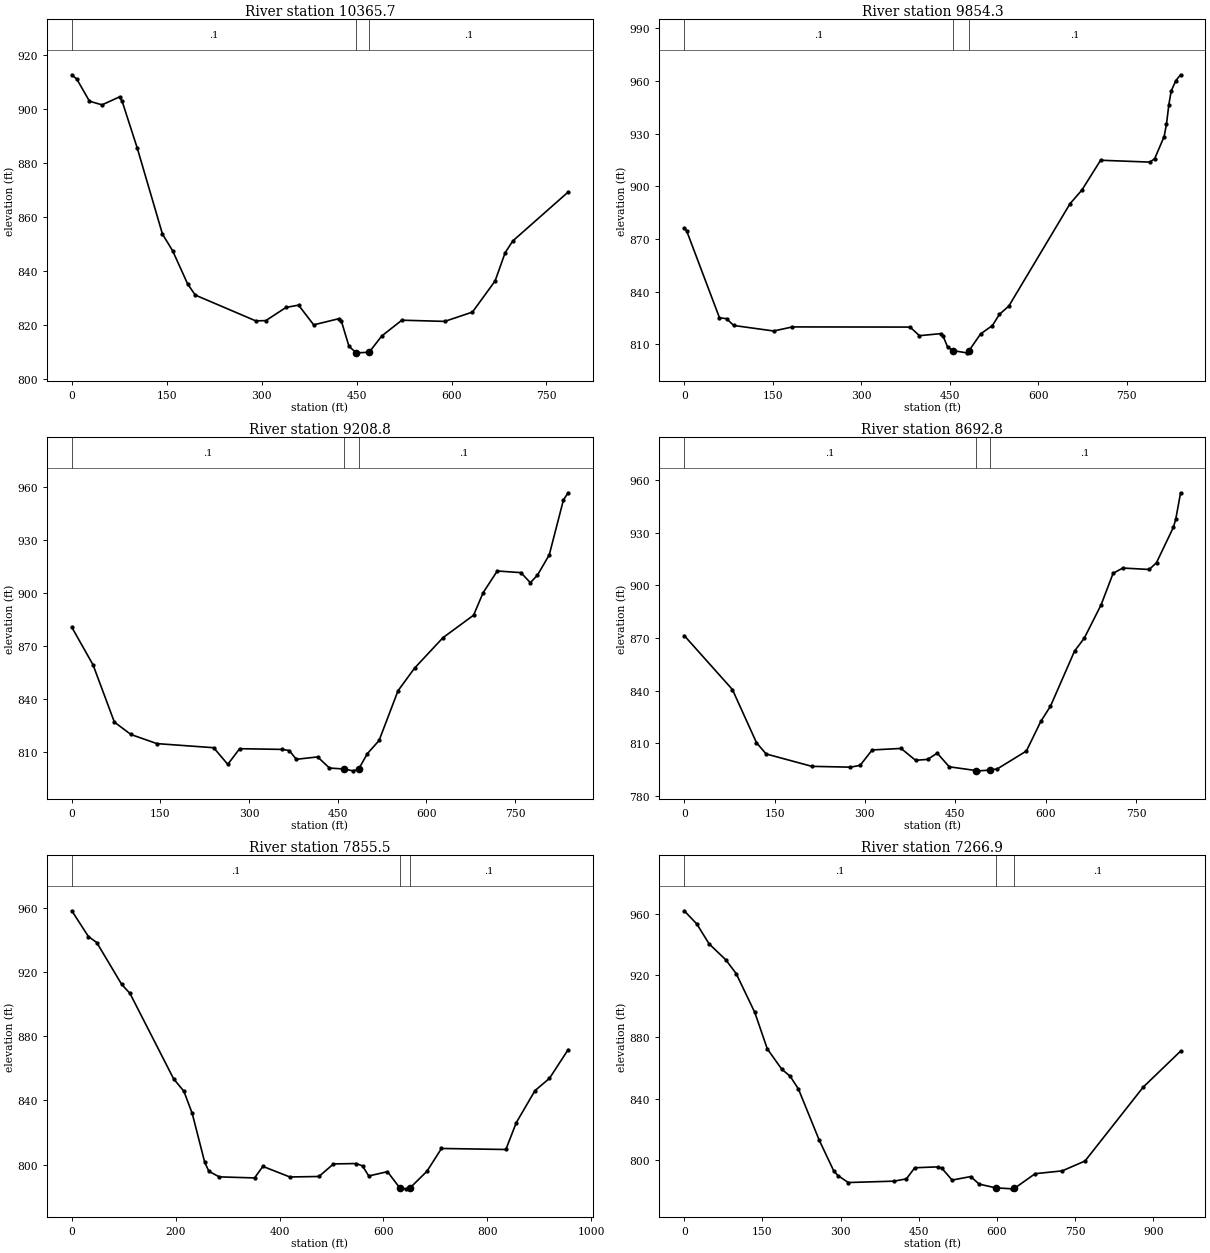
Type RM Length L Ch R = 1 ,10365.7 ,515.3,511.4,507.5
XS GIS Cut Line= 2
     1808682.166      381745.323     1809441.715      381940.635
#Sta/Elev= 30
       0  912.72       8   911.1    27.9  902.94    47.8  901.59    75.6  904.56
    79.6  902.86   103.5  885.54   143.3  853.72   159.2  847.64   183.1  835.26
   195.1  831.18   290.6  821.64   306.5  821.72   338.4   826.6   358.3  827.46
   382.2  820.16     422  822.44     426   821.5   437.9  812.23     449  809.89
   449.8   809.8   469.8  810.01   489.7  816.04   521.5  821.88   589.2  821.44
     633  824.88   668.8   836.4   684.7  846.86   696.7   851.2   784.3  869.33
#Mann= 3 , 0 , 0
       0      .1       0     449    .045       0   469.8      .1       0
Bank Sta=449,469.8
XS Rating Curve= 0 ,0
Exp/Cntr=0.3,0.1

Type RM Length L Ch R = 1 ,9854.3  ,644.8,645.5,646.2
XS GIS Cut Line= 2
     1808569.319      382316.069     1809406.992      382396.365
#Sta/Elev= 30
       0   876.3       4   874.7    59.8  825.04    71.8  824.56    83.8  820.68
   151.6  817.53   183.5  819.85   382.9  819.76   398.8  814.86   434.7  816.01
   438.7  814.72   446.7  808.29   456.5   806.3   478.6  805.08   482.6  806.22
   502.5  815.88   522.5  820.64   534.4  827.02   550.4  831.77   654.1  890.08
     674  897.75   705.9  914.82   789.7  913.76   797.6  915.76   813.6  928.33
   817.6  935.46   821.6  946.55   825.6  954.31   833.5  960.24   841.5  963.52
#Mann= 3 , 0 , 0
       0      .1       0   456.5    .045       0   482.6      .1       0
Bank Sta=456.5,482.6
XS Rating Curve= 0 ,0
Exp/Cntr=0.3,0.1

Type RM Length L Ch R = 1 ,9208.8  ,520.6,516,511.4
XS GIS Cut Line= 2
     1808497.704       382943.24     1809331.038      383047.406
#Sta/Elev= 30
       0  880.58      36  859.27      72  826.97     100  819.95     144  814.79
     240  812.47   263.9  803.06   283.9  811.91   355.9  811.52   367.9  810.87
   379.9  805.92   415.9  807.27   435.9  800.99   459.9  800.44   475.9   799.4
   485.2  800.32   499.9  809.06   519.9  816.57   551.9  844.66   579.9  857.46
   627.9  874.65   679.8  887.39   695.8  900.04   719.8  912.37   759.8  911.44
   775.8  905.76   787.8     910   807.8  921.52   831.8  952.59   839.8  956.58
#Mann= 3 , 0 , 0
       0      .1       0   459.9    .045       0   485.2      .1       0
#XS Ineff= 2 , 0
       0   415.9                       0
Permanent Ineff=
       F       F
Bank Sta=459.9,485.2
XS Rating Curve= 0 ,0
Exp/Cntr=0.3,0.1

Type RM Length L Ch R = 1 ,8692.8  ,833.2,837.3,841.4
XS GIS Cut Line= 2
       1808432.6      383542.198     1809255.083      383492.285
#Sta/Elev= 30
       0  871.45      80  840.68     120  810.36     136  803.94     212  796.88
     276  796.42     292  797.43     312  806.23     360  807.09     384  800.34
     404  800.84     420   804.4     440  796.62     484  794.51     488  794.32
   506.8  794.69     520  795.49     568  805.61     592  822.54     608  831.16
     648  862.62     664  869.91     692  888.93     712  906.94     728  909.93
     772  909.12     784  913.01     812  933.14     816  937.84     824  952.84
#Mann= 3 , 0 , 0
       0      .1       0     484    .045       0   506.8      .1       0
#XS Ineff= 2 , 0
       0     420                       0
Permanent Ineff=
       F       F
Bank Sta=484,506.8
XS Rating Curve= 0 ,0
Exp/Cntr=0.3,0.1

Type RM Length L Ch R = 1 ,7855.5  ,584.9,588.6,592.2
XS GIS Cut Line= 2
     1808232.947      384264.854     1809183.468      384364.681
#Sta/Elev= 30
       0  957.97      32  941.93      48  938.22      96  912.17     112  906.54
     196   853.4   215.9   845.6   231.9  831.79   255.9  801.44   263.9  795.82
   283.9  792.34   351.9  791.68   367.9  798.86   419.9  792.27   475.9  792.58
   503.9   800.4   547.9  800.63   559.8  799.14   571.8   792.9   607.8  795.58
   631.8  785.35   643.8  784.89   651.8  785.64   683.8  795.81   711.8  810.02
   835.8  809.38   855.8  826.05   891.8     846   919.8   853.7   955.8  871.55
#Mann= 3 , 0 , 0
       0      .1       0   631.8    .045       0   651.8      .1       0
#XS Ineff= 2 , 0
       0     535                       0
Permanent Ineff=
       F       F
Bank Sta=631.8,651.8
XS Rating Curve= 0 ,0
Exp/Cntr=0.3,0.1

Type RM Length L Ch R = 1 ,7266.9  ,394.7,404.4,414.1
XS GIS Cut Line= 2
     1808183.034      384759.646     1809105.343      384996.191
#Sta/Elev= 30
       0     962    23.9  953.54    47.8  940.51    79.7  930.16    99.6  921.26
   135.4  895.97   159.4  872.29   187.2  859.07   203.2  854.55   219.1  846.26
     259  813.01   286.8  793.09   294.8  790.05   314.7   785.5   402.4  786.39
   426.3  787.88   442.2   795.1     486  795.66     494  794.86   513.9  787.09
   549.8  789.38   565.7  784.47   597.6  782.05   629.4   781.4   633.4  781.71
   673.3  791.25   725.1  793.07   768.9  799.49   880.4  847.44   952.2  870.85
#Mann= 3 , 0 , 0
       0      .1       0   597.6    .045       0   633.4      .1       0
#XS Ineff= 2 , 0
       0   482.1                       0
Permanent Ineff=
       F       F
Bank Sta=597.6,633.4
XS Rating Curve= 0 ,0
Exp/Cntr=0.3,0.1

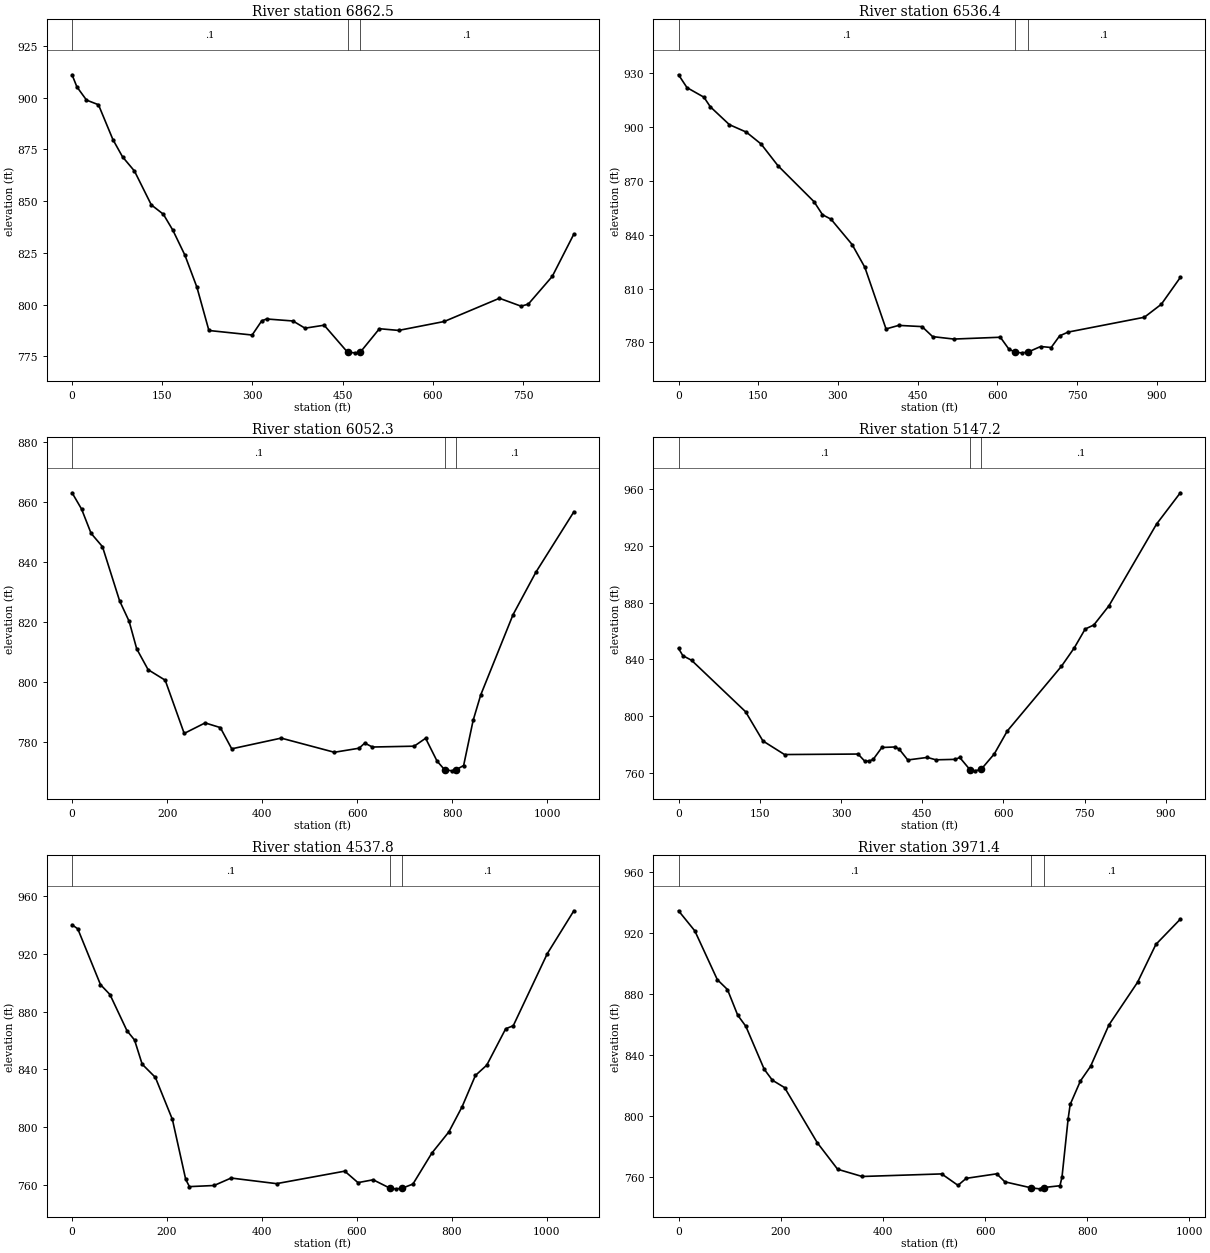
Type RM Length L Ch R = 1 ,6862.5  ,329.7,326.1,322.3
XS GIS Cut Line= 2
     1808254.649      385000.531     1808925.222      385497.493
#Sta/Elev= 30
       0   911.1       8  905.27      24  898.87    43.9  896.62    67.9   879.8
    83.9  871.46   103.8  864.56   131.8  848.21   151.8  843.71   167.7  835.94
   187.7   823.9   207.7  808.37   227.6   787.5   299.5  785.31   315.5  792.19
   323.5  793.07   367.4   792.1   387.4  788.62   419.3  790.06   458.4  776.93
   471.2   776.7   479.2  776.95   511.2  788.36   543.1  787.54     619  791.85
   710.8  803.08   746.8  799.25   758.8  800.24   798.7  813.66   834.6   834.1
#Mann= 3 , 0 , 0
       0      .1       0   458.4    .045       0   479.2      .1       0
Bank Sta=458.4,479.2
XS Rating Curve= 0 ,0
Exp/Cntr=0.3,0.1

Type RM Length L Ch R = 1 ,6536.4  ,474.8,484.1,493.4
XS GIS Cut Line= 2
      1807959.51      385282.649     1808792.843      385727.528
#Sta/Elev= 30
       0  928.96    15.9  921.81    47.8  916.48    59.8  911.16    95.7   901.2
   127.6  897.05   155.4  890.43   187.3   878.3   255.1  858.32     271  851.07
     287  848.59   326.8  834.46   350.8  821.75   390.6   787.5   414.5  789.48
   458.4   788.8   478.3  783.23   518.2  781.87   605.8  782.88   621.8   776.3
   633.8  774.53   645.7   774.2   657.7  774.61   681.6  777.72   701.5  777.17
   717.4  783.65   733.4  785.75   876.9  794.01   908.8  801.23   944.6  816.17
#Mann= 3 , 0 , 0
       0      .1       0   633.8    .045       0   657.7      .1       0
#XS Ineff= 2 , 0
       0     597                       0
Permanent Ineff=
       F       F
Bank Sta=633.8,657.7
XS Rating Curve= 0 ,0
Exp/Cntr=0.3,0.1

Type RM Length L Ch R = 1 ,6052.3  ,892.3,905.1,917.8
XS GIS Cut Line= 2
     1807763.329      385392.458     1808451.263       386193.24
#Sta/Elev= 30
       0  862.98      20  857.55      40  849.46      64     845     100  826.96
     120  820.15     136  810.95     160     804   195.9   800.5   235.9  782.75
   279.9  786.26   311.9   784.7   335.9  777.62   439.9  781.19   551.8  776.47
   603.8  777.82   615.8  779.53   631.8  778.22   719.8   778.5   743.8  781.14
   767.8  773.55   783.8  770.64   799.8  770.28   807.8  770.62   823.8  772.06
   843.8  787.11   859.8   795.6   927.7  822.33   975.7  836.47  1055.7  856.63
#Mann= 3 , 0 , 0
       0      .1       0   783.8    .045       0   807.8      .1       0
Bank Sta=783.8,807.8
XS Rating Curve= 0 ,0
Exp/Cntr=0.3,0.1

Type RM Length L Ch R = 1 ,5147.2  ,622.7,609.4,595.9
XS GIS Cut Line= 2
      1807309.77      385440.201     1807518.104      386342.979
#Sta/Elev= 30
       0  847.72       8  842.61      24   839.4   123.8   803.2   155.8  782.64
   195.7  773.08   331.5  773.43   343.4  768.59   351.4  768.44   359.4  769.66
   375.4  778.04   399.4   778.4   407.3  776.93   423.3  769.27   459.3  771.06
   475.2  769.37   511.2   769.7   519.2  771.03   538.7  762.14   547.1  761.62
   558.7  762.64   583.1  773.57     607  789.65   706.9  835.12   730.8  848.17
   750.8  861.36   766.8  864.21   794.7   877.7   882.6  935.19   926.5   957.2
#Mann= 3 , 0 , 0
       0      .1       0   538.7    .045       0   558.7      .1       0
#XS Ineff= 2 , 0
       0     487                       0
Permanent Ineff=
       F       F
Bank Sta=538.7,558.7
XS Rating Curve= 0 ,0
Exp/Cntr=0.3,0.1

Type RM Length L Ch R = 1 ,4537.8  ,567.4,566.4,565.3
XS GIS Cut Line= 2
     1806439.545      385772.233     1807168.711      386538.292
#Sta/Elev= 30
       0  940.01      12  937.24    59.9  898.63    79.8   891.8   115.7  866.79
   131.7  860.34   147.7  843.65   175.6  834.48   211.5  805.38   239.5  763.96
   247.4  758.96   299.3  759.74   335.2   764.9     431  761.02   574.7  769.66
   602.6  761.73   634.6  763.69   670.5   757.8   682.5  757.43   694.4  757.69
   718.4  760.74   758.3  782.15   794.2  796.83   822.1  814.23   850.1  835.83
     874  842.95   913.9  868.12   929.9  870.23  1001.7  920.12  1057.6  949.71
#Mann= 3 , 0 , 0
       0      .1       0   670.5    .045       0   694.4      .1       0
#XS Ineff= 2 , 0
       0     570                       0
Permanent Ineff=
       F       F
Bank Sta=670.5,694.4
XS Rating Curve= 0 ,0
Exp/Cntr=0.3,0.1

Type RM Length L Ch R = 1 ,3971.4  ,426.5,437.4,448.3
XS GIS Cut Line= 2
     1806044.579      386210.601     1806749.874      386894.194
#Sta/Elev= 30
       0  934.71    31.9  921.54    75.9   889.6    95.8  883.11   115.8  866.34
   131.8     859   167.7  830.91   183.7  823.72   207.6  818.88   271.5  782.82
   311.4   765.4   359.4  760.66   515.1  762.35     547  754.86     563  759.44
   622.9  762.42   638.8  757.15   690.8  753.18   706.7  752.57   714.7  753.43
   746.6   754.6   750.6  760.32   762.6  798.45   766.6  807.85   786.6  823.21
   806.5  832.81   842.5  859.96   898.4  887.82   934.3  912.66   982.2  929.23
#Mann= 3 , 0 , 0
       0      .1       0   690.8    .045       0   714.7      .1       0
#XS Ineff= 2 , 0
       0     503                       0
Permanent Ineff=
       F       F
Bank Sta=690.8,714.7
XS Rating Curve= 0 ,0
Exp/Cntr=0.3,0.1

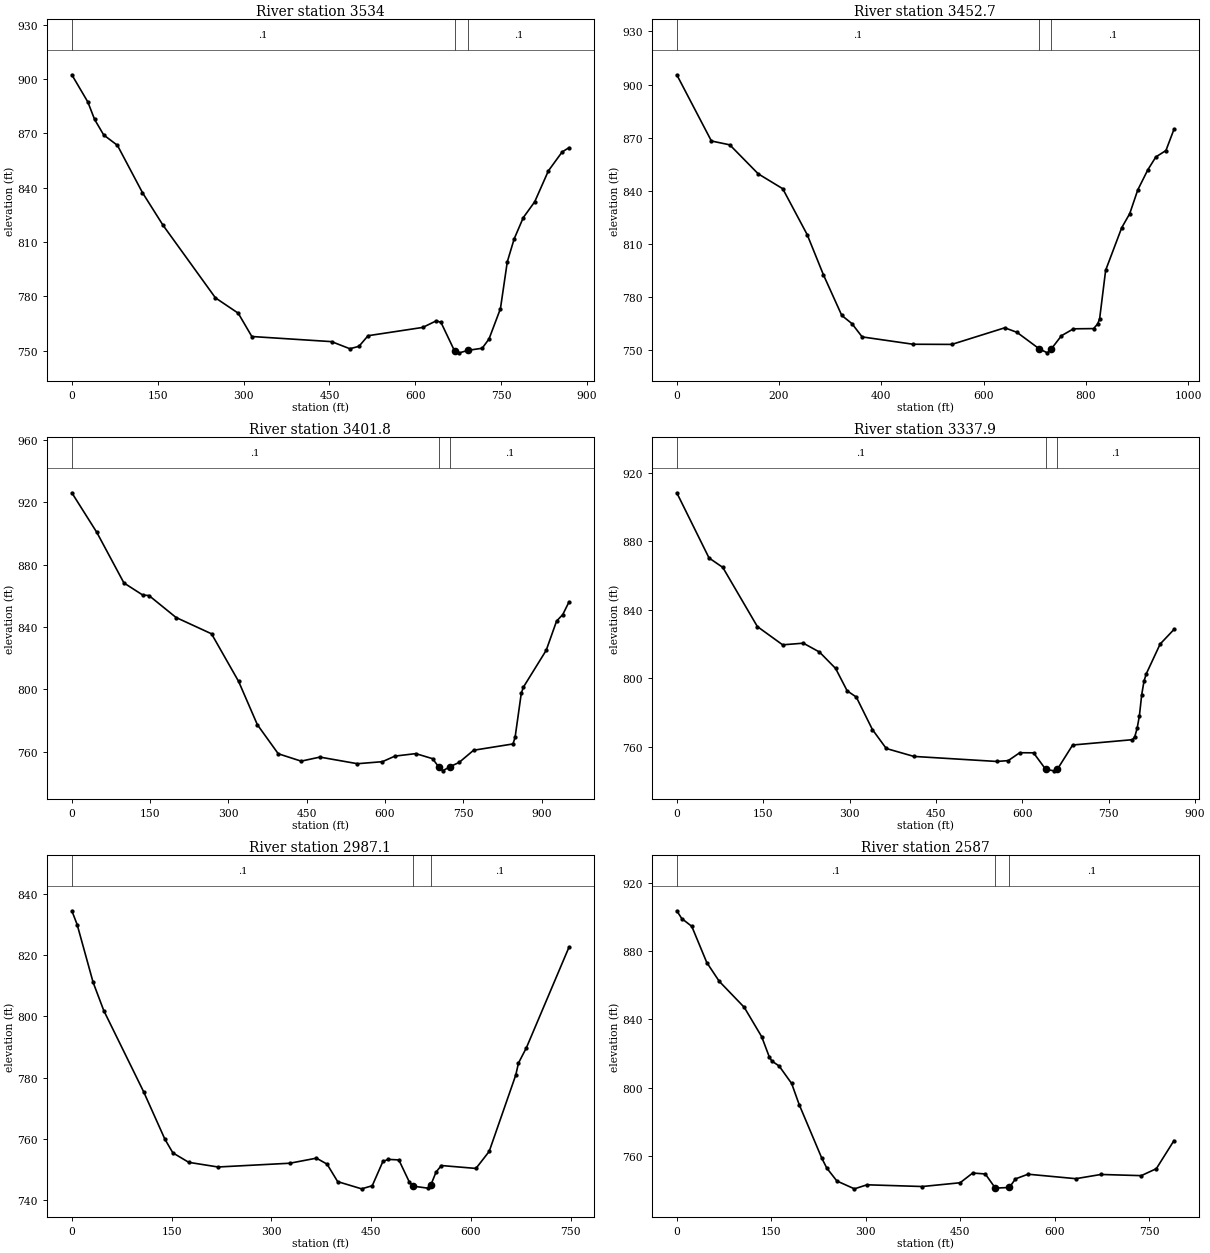
Type RM Length L Ch R = 1 ,3534    ,67,81.3,106.2
XS GIS Cut Line= 3
     1805738.156      386451.486      1806190.63       386899.62
     1806279.605      387113.379
#Sta/Elev= 30
       0  902.26    27.9  887.27    39.8  877.59    55.7  869.04    79.6  863.34
   123.4  837.21   159.2  819.28   250.8  779.18   290.6  770.72   314.4  757.85
   453.7  755.02   485.6  751.11   501.5  752.42   517.4  758.29     613  762.87
   636.8  766.54   644.8  765.62   668.8  749.68   676.8  748.84   692.7  750.26
   716.7  751.37   728.6  756.44   748.6  773.19   760.6  799.06   772.6  811.72
   788.5  823.44   808.5  832.19   832.4  849.27   856.4  859.68   868.4  862.04
#Mann= 3 , 0 , 0
       0      .1       0   668.8    .045       0   692.7      .1       0
Bank Sta=668.8,692.7
XS Rating Curve= 0 ,0
Exp/Cntr=0.3,0.1

Type RM Length L Ch R = 1 ,3452.7  ,53.1,50.9,42.2
XS GIS Cut Line= 4
     1805604.041      386501.833     1806143.972      386942.806
      1806113.59      386988.813     1806276.784      387136.382
#Sta/Elev= 30
       0  905.54    67.7  868.15   103.6  865.98   159.3   849.6   207.2   841.2
     255  815.29   286.8  792.58   322.7  769.64   342.6  765.02   362.5  757.53
   462.1  753.38   537.8  753.29   641.4  762.67   665.3  760.11   709.2  750.71
   724.7  748.53   732.6  750.81   752.3   758.2   775.8  762.09   815.1  762.22
     823  764.81   826.9  767.68   838.7  795.16   870.1  819.16   885.8  827.14
   901.6  840.58   921.2  851.89   936.9  859.15   956.6  862.76   972.3  874.72
#Mann= 3 , 0 , 0
       0      .1       0   709.2    .045       0   732.6      .1       0
Bank Sta=709.2,732.6
XS Rating Curve= 0 ,0
Exp/Cntr=0.3,0.1

Type RM Length L Ch R = 1 ,3401.8  ,88.3,63.9,35.2
XS GIS Cut Line= 4
     1805554.562      386484.472     1806089.284      386921.972
     1806077.131      386971.451     1806227.305      387119.021
#Sta/Elev= 30
       0  926.11    47.9  900.67    99.8  868.24   135.8   860.5   147.8  860.17
   199.7  846.08   267.6  835.62   319.5  805.05   355.4   777.3   395.4  758.66
   439.3  753.92   475.2  756.52   547.1  752.27     595  753.58     619  757.16
   658.9  758.75   690.9  755.52   702.6  750.34   710.5   747.7   723.8  750.29
   741.8  753.07   769.6  760.91   845.1  764.96   849.1  769.16     861  797.54
     865  801.39   908.7  825.03   928.6   843.8   940.5     848   952.4   856.1
#Mann= 3 , 0 , 0
       0      .1       0   702.6    .045       0   723.8      .1       0
Bank Sta=702.6,723.8
XS Rating Curve= 0 ,0
Exp/Cntr=0.3,0.1

Type RM Length L Ch R = 1 ,3337.9  ,348.7,350.8,352.9
XS GIS Cut Line= 2
     1805533.078      386535.037     1806187.374      387098.188
#Sta/Elev= 30
       0  908.25      56  870.16    79.9  864.65   139.9  830.09   183.8  819.42
   219.8  820.38   247.8  815.19   275.8  805.61   295.8  792.57   311.7   788.9
   339.7  769.91   363.7  758.86   411.6  754.23   555.5  751.28   575.5  751.77
   595.5  756.38   619.5  756.32   640.7  746.63   655.4   745.8   660.7  746.64
   687.4  760.89   791.3     764   795.3  765.79   799.3  770.56   803.3  777.96
   807.3  790.29   811.3  798.25   815.3  802.54   839.3  819.87   863.3  828.39
#Mann= 3 , 0 , 0
       0      .1       0   640.7    .045       0   660.7      .1       0
Bank Sta=640.7,660.7
XS Rating Curve= 0 ,0
Exp/Cntr=0.3,0.1

Type RM Length L Ch R = 1 ,2987.1  ,398.3,400,401.6
XS GIS Cut Line= 2
     1805399.614      386814.984     1805922.617      387348.839
#Sta/Elev= 30
       0  834.52       8     830      32  811.12      48   801.9   107.9  775.38
   139.9  759.86   151.9  755.39   175.8   752.3   219.8  750.78   327.7  752.01
   367.7  753.67   383.7  751.71   399.6     746   435.6  743.64   451.6  744.65
   467.6  752.58   475.6  753.27   491.6  753.09   507.6  745.76   513.4  744.51
   535.5  743.85   539.5   744.8   547.5  749.11   555.5  751.26   607.5  750.31
   627.4  755.87   667.4  780.86   671.4  784.73   683.4  789.78   747.4  822.64
#Mann= 3 , 0 , 0
       0      .1       0   513.4    .045       0   539.5      .1       0
Bank Sta=513.4,539.5
XS Rating Curve= 0 ,0
Exp/Cntr=0.3,0.1

Type RM Length L Ch R = 1 ,2587    ,518.7,529.7,540.6
XS GIS Cut Line= 3
     1805089.284      387099.273     1805258.555       387209.95
     1805648.095      387649.403
#Sta/Elev= 30
       0  903.69     7.9  899.12    23.8  894.57    47.6  873.35    67.4  862.33
   107.1  847.08   134.8  829.84   146.7  818.16   150.7  815.66   162.6   812.6
   182.4  802.39   194.3  790.06   230.2  758.64   238.2  752.78   254.2  745.21
   282.1   740.6   302.1  742.97     390  741.96   449.9  744.17   469.9  749.87
   489.9  749.33   505.8  741.04   528.1  741.39   537.8  746.44   557.8  749.18
   633.7  746.56   673.6  749.03   737.6  748.34   761.5  752.42   789.5  768.88
#Mann= 3 , 0 , 0
       0      .1       0   505.8    .045       0   528.1      .1       0
#XS Ineff= 2 , 0
       0                     670       0
Permanent Ineff=
       F       F
Bank Sta=505.8,528.1
XS Rating Curve= 0 ,0
Exp/Cntr=0.3,0.1

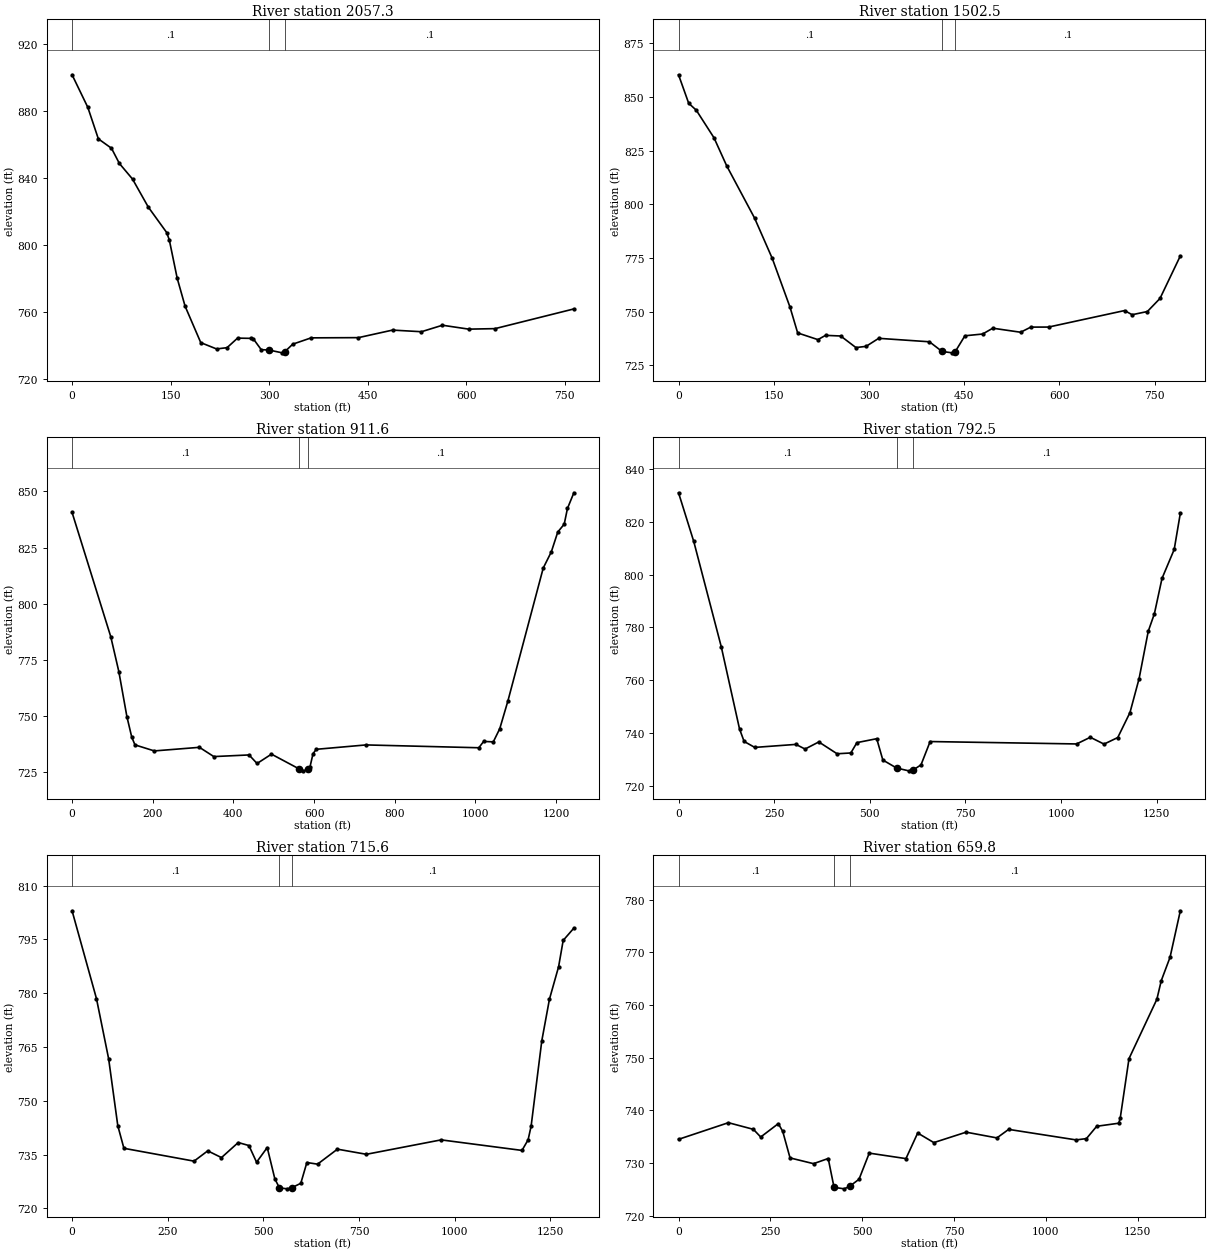
Type RM Length L Ch R = 1 ,2057.3  ,547,554.8,562.4
XS GIS Cut Line= 2
     1804913.503      387389.854     1805132.253      388121.625
#Sta/Elev= 30
       0  901.36      24   881.9      40  863.13      60  857.52      72  848.45
      92  839.15     116  822.43     144  807.25     148  802.84     160  780.01
     172  763.33   195.9  741.55   219.9  737.79   235.9  738.54   251.9  744.24
   271.9   744.1   275.9  743.82   287.9  737.36   299.9  737.12   319.9  735.46
   323.9  736.18   335.9  740.63   363.9   744.4   435.9  744.53   487.8  749.03
   531.8  748.06   563.8  751.93   603.8   749.6   643.8   749.9   763.8  761.66
#Mann= 3 , 0 , 0
       0      .1       0   299.9    .045       0   323.9      .1       0
Bank Sta=299.9,323.9
XS Rating Curve= 0 ,0
Exp/Cntr=0.3,0.1

Type RM Length L Ch R = 1 ,1502.5  ,580,590.9,601.8
XS GIS Cut Line= 2
      1804499.44      387410.688     1804481.211      388201.052
#Sta/Elev= 30
       0  860.33      16  847.07      28  843.82    55.9  830.98    75.9  817.92
   119.8  793.61   147.7  774.81   175.7  752.08   187.7  740.13   219.6  737.01
   231.6     739   255.5   738.7   279.5  733.31   295.5  733.88   315.4  737.62
   395.3  736.01   415.2   731.5   431.2  730.86   435.2  731.05   451.2   738.8
   479.1  739.62   495.1  742.33     539  740.45     555  742.84     583  742.86
   702.7  750.54   714.7  748.61   738.7   750.1   758.6   756.2   790.6  775.99
#Mann= 3 , 0 , 0
       0      .1       0   415.2    .045       0   435.2      .1       0
#XS Ineff= 2 , 0
       0     243                       0
Permanent Ineff=
       F       F
Bank Sta=415.2,435.2
XS Rating Curve= 0 ,0
Exp/Cntr=0.3,0.1

Type RM Length L Ch R = 1 ,911.6   ,135.6,119.1,86.4
XS GIS Cut Line= 4
     1804305.864      387306.955     1804043.277      387467.545
     1803882.687      387790.896     1803880.517      388365.983
#Sta/Elev= 30
       0  840.64    95.9  785.31   115.9  769.79   135.9  749.72   147.9  740.59
   155.9  737.12   203.9  734.43   315.7  736.03   351.4  731.91   438.7  732.64
   458.6  728.83   494.3  732.99   561.7  726.53   573.6  725.56   585.5  726.31
   589.5   727.1   597.4  733.24   605.4  735.15   728.7   737.1  1008.3  735.84
  1020.3  738.66  1044.2  738.46  1060.2  744.32  1080.2  756.56    1168  815.88
    1188  823.07    1204   831.9    1220  835.42    1228   842.4  1243.9  849.39
#Mann= 3 , 0 , 0
       0      .1       0   561.7    .045       0   585.5      .1       0
#XS Ineff= 2 , 0
       0   315.7                       0
Permanent Ineff=
       F       F
Bank Sta=561.7,585.5
XS Rating Curve= 0 ,0
Exp/Cntr=0.3,0.1

Type RM Length L Ch R = 1 ,792.5   ,74,77,93.9
XS GIS Cut Line= 3
     1804271.576       387237.51     1803866.628      387499.229
     1803822.357      388327.354
#Sta/Elev= 30
       0  830.98    39.8  812.52   111.6  772.68   159.4  741.49   171.4  736.75
   199.2  734.49   306.8  735.63   330.7  733.87   366.6  736.56   414.4  732.08
   450.3  732.38   466.2   736.3     518  737.79     534   729.7   569.9  726.68
   601.6  725.61   613.7  725.98   633.7  727.87   657.6  736.71  1040.4   735.8
  1076.2  738.33  1112.1  735.74    1148  738.23  1179.9  747.69  1203.8   760.6
  1227.7  778.52  1243.7  785.13  1263.6  798.52  1295.5  809.51  1311.5  823.22
#Mann= 3 , 0 , 0
       0      .1       0   569.9    .045       0   613.7      .1       0
#XS Ineff= 2 , 0
       0     514                       0
Permanent Ineff=
       F       F
Bank Sta=569.9,613.7
XS Rating Curve= 0 ,0
Exp/Cntr=0.3,0.1

Type RM Length L Ch R = 1 ,715.6   ,46.7,55.7,67.1
XS GIS Cut Line= 3
     1804213.416      387215.809     1803808.468      387477.528
     1803764.197      388305.653
#Sta/Elev= 30
       0     803    63.8   778.5    95.6  761.73   119.5  743.08   135.5  736.78
   318.8   733.2   354.6  736.07   390.5  734.19   434.3  738.39   462.2  737.55
   482.2   732.9   510.1  736.99     530  728.25     542  725.76   561.9  725.48
   573.9  725.78   597.8  727.02   613.7  732.82   641.6  732.36   693.5  736.54
   769.2  735.11   964.6  739.13  1175.9  736.19  1191.9  739.14  1199.8  742.96
  1227.7  766.76  1247.7  778.35  1271.6   787.4  1283.6  794.74  1311.5  798.16
#Mann= 3 , 0 , 0
       0      .1       0     542    .045       0   573.9      .1       0
#XS Ineff= 2 , 0
       0     510                       0
Permanent Ineff=
       F       F
Bank Sta=542,573.9
XS Rating Curve= 0 ,0
Exp/Cntr=0.3,0.1

Type RM Length L Ch R = 1 ,659.8   ,666.3,659.8,653.2
XS GIS Cut Line= 2
     1803889.284      387091.243     1803498.572      388400.705
#Sta/Elev= 30
       0   734.5   135.8  737.66   203.8   736.4   223.8  734.94   271.7  737.48
   283.7  736.02   303.7  730.97   367.6  729.88   407.6  730.86   423.5  725.38
   451.5   725.1   467.4  725.65   491.5  726.92   519.4  731.88   619.3  730.84
   651.3   735.7   695.2  733.88   783.2  735.86     867  734.77     899  736.39
  1082.8  734.39  1110.8  734.64  1138.8  736.98  1198.7  737.56  1202.7  738.46
  1226.7  749.82  1302.6  761.09  1314.6  764.63  1338.5  769.07  1366.5   777.9
#Mann= 3 , 0 , 0
       0      .1       0   423.5    .045       0   467.4      .1       0
Bank Sta=423.5,467.4
XS Rating Curve= 0 ,0
Exp/Cntr=0.3,0.1

Chan Stop Cuts=-1
Use User Specified Reach Order=0
Composite Channel Slope=5